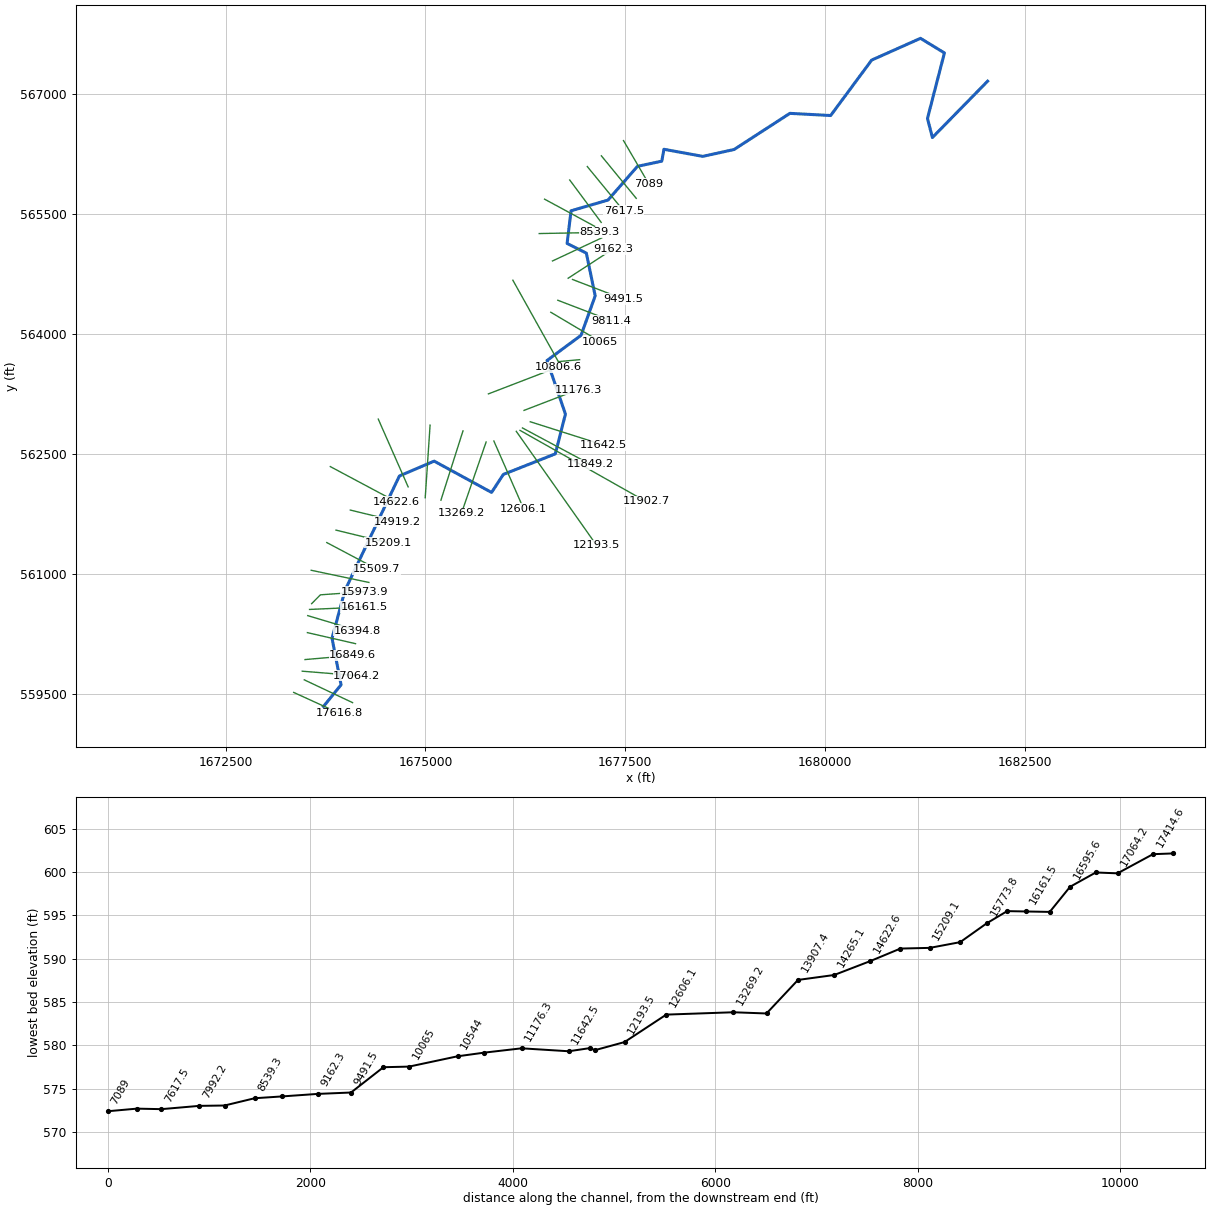
--- FivTwentyC.prj (project) ---

Proj Title=FivTwentyC
Current Plan=p01
Default Exp/Contr=0,0
English Units
Geom File=g01
Flow File=f01
Plan File=p01
BEGIN DESCRIPTION:
AMEC Environment & Infrastructure, 2013
Projection: NAD 1983 State Plane West Virginia South FIPS 4702 (US Feet)
Vertical Datum: NAVD 1988
END DESCRIPTION:
DSS Export Rating Curves= 0
DSS Export Rating Curve Sorted= 0
DSS Export Volume Flow Curves= 0
DXF OffsetX= 0
DXF OffsetY= 0
DXF ScaleX= 0
DXF ScaleY= 0

--- FivTwentyC.p01 (plan) ---

Plan Title=Floodplain
Program Version=4.00
Geom File=g01
Flow File=f01
K Sum by GR=0
Std Step Tol=0.01
Critical Tol=0.01
Num of Std Step Trials=20
Max Error Tol=0.3
Flow Tol Ratio=0.001
Split Flow NTrial=30
Split Flow Tol=0.02
Split Flow Ratio=0.02
Log Output Level=0
Friction Slope Method=1
Unsteady Friction Slope Method=2
Unsteady Bridges Friction Slope Method=1
Global Log Level=0
CheckData=False
Run HTab=0
Run UNet=0
Run PostProcess=0
UNET Theta=0
UNET Theta Warmup=0
UNET ZTol=0
UNET ZSATol=0
UNET MxIter=0
UNET MaxInSteps=0
UNET DtIC=0
UNET DtMin=0
UNET MaxCRTS=0
UNET WFStab=0
UNET SFStab=0
UNET WFX=0
UNET SFX=0
UNET DSS MLevel=0
UNET DZMax Abort=0
UNET Convert EG Bridges=0
UNET Use Existing IB Tables=0
UNET Froude Limit=0
UNET Froude Power=0
Write IC File=0
Echo Input=False
Echo Output=False
Write Detailed=0

--- FivTwentyC.f01 (steady flow) ---

Flow Title=USGS Regress. Eqn. (2010) - Western-Plateaus
Program Version=4.10
Number of Profiles= 1
Profile Names=P100yr
River Rch & RM=FivTwentyC,Main            ,17616.8
    1169
River Rch & RM=FivTwentyC,Main            ,14622.6
    1258
River Rch & RM=FivTwentyC,Main            ,14265.1
    1314
River Rch & RM=FivTwentyC,Main            ,12193.5
    1370
River Rch & RM=FivTwentyC,Main            ,11902.7
    1844
River Rch & RM=FivTwentyC,Main            ,5468
    1933
River Rch & RM=FivTwentyC,Main            ,5040.3
    3015
River Rch & RM=FivTwentyC,Main            ,1662.2
    3037
River Rch & RM=FivTwentyC,Main            ,281
    3064
River Rch & RM=FivTwentyC,Main            ,7.9
    3087
Boundary for River Rch & Prof#=FivTwentyC,Main            , 1
Up Type= 0
Dn Type= 3
Dn Slope=0.0013
DSS Import GetInterval= 0
DSS Import GetPeak= 0
DSS Import FillOption= 0

--- FivTwentyC.g01 (geometry) ---

Geom Title=USGS 3m DEM
Program Version=4.10

River Reach=FivTwentyC      ,Main
Reach XY= 30
     1673724.739       559340.44     1673944.136      559610.558
     1673831.288      560193.241     1673992.964      560792.199
     1674674.387      562224.491       1675109.5      562410.038
     1675827.816      562018.327     1675975.386      562244.022
     1676625.743      562500.911     1676752.295      562999.013
     1676521.827      563669.586     1676947.608       563984.69
     1677124.691       564478.18     1677014.014      565013.336
     1676773.129       565134.43     1676822.608      565543.284
     1677284.847      565677.399     1677653.337      566099.274
     1677958.025      566164.378     1677985.368      566312.815
     1678471.045      566224.274     1678862.972      566310.211
     1679561.207       566762.54     1680071.624      566735.457
     1680584.819      567429.207      1681195.93      567701.429
     1681495.235       567518.79      1681283.43      566699.346
     1681344.541      566459.763      1682036.27      567165.638

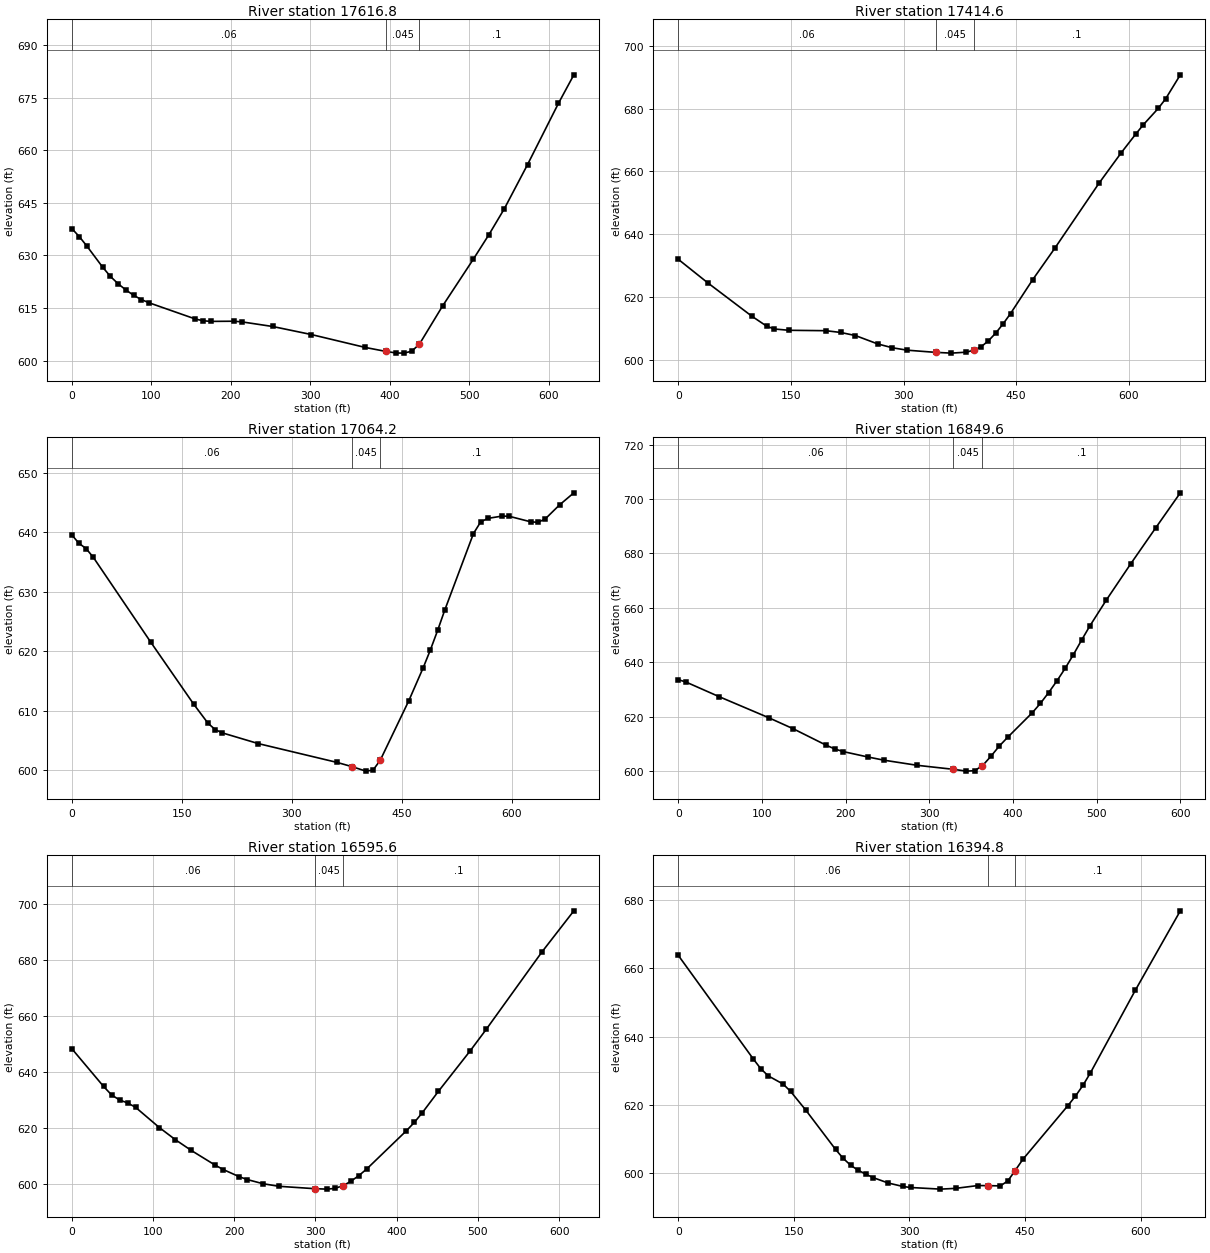
Type RM Length L Ch R = 1 ,17616.8 ,198.5,202.3,217.5
XS GIS Cut Line= 2
     1673351.325      559515.745     1673925.823      559253.276
#Sta/Elev= 30
       0  637.68     9.7  635.31    19.4  632.55    38.9  626.64    48.6  624.02
    58.3  621.92      68  620.17    77.7  618.65    87.4  617.43    97.2   616.5
   155.5  611.87   165.2  611.37   174.9  611.19   204.1  611.24   213.8  611.06
   252.6  609.74   301.2  607.45   369.2  603.76   394.7602.6464   408.1  602.18
   417.8  602.14   427.6  602.68   437.3  604.69   466.4  615.56   505.3  628.98
   524.7   635.9   544.2  643.34   573.3  655.89   612.2  673.37   631.6  681.51
#Mann= 3 , 0 , 0
       0     .06       0   394.7    .045       0   437.3      .1       0
Bank Sta=394.7,437.3
XS Rating Curve= 0 ,0
Exp/Cntr=0.3,0.1

Type RM Length L Ch R = 1 ,17414.6 ,346.8,350.3,339.5
XS GIS Cut Line= 2
     1673483.938      559672.817     1674088.678      559387.643
#Sta/Elev= 30
       0  631.97    39.3  624.46    98.3  613.77     118  610.61   127.8  609.75
   147.5  609.33   196.6   609.2   216.3  608.64     236  607.65   265.5  604.99
   285.1  603.76   304.8  602.99   342.6 602.296   363.8  602.05   383.5  602.35
   393.3  602.97   403.1  604.04     413  605.96   422.8  608.44   432.6  611.37
   442.5  614.66     472  625.46   501.5   635.5   560.4  656.24     590  665.95
   609.6  671.99   619.4  674.87   639.1  680.04   648.9  683.07   668.6  690.77
#Mann= 3 , 0 , 0
       0     .06       0   342.6    .045       0   393.3      .1       0
Bank Sta=342.6,393.3
XS Rating Curve= 0 ,0
Exp/Cntr=0.3,0.1

Type RM Length L Ch R = 1 ,17064.2 ,210.6,214.7,221.2
XS GIS Cut Line= 2
     1673458.518      559781.115     1674141.127      559725.859
#Sta/Elev= 30
       0  639.57     9.8  638.15    19.6  637.26    29.4  635.79   107.6  621.55
   166.3   611.1   185.9  607.88   195.7  606.82   205.4  606.27   254.4  604.47
     362   601.3   382.3600.5911   401.1  599.84   410.9  600.01   420.7  601.66
   459.8  611.71   479.4  617.25   489.2  620.25     499   623.5   508.7  626.91
   547.9   639.8   557.7  641.74   567.4  642.34     587  642.73   596.8  642.69
   626.1  641.76   635.9  641.68   645.7  642.24   665.3  644.61   684.8  646.64
#Mann= 3 , 0 , 0
       0     .06       0   382.3    .045       0   420.7      .1       0
Bank Sta=382.3,420.7
XS Rating Curve= 0 ,0
Exp/Cntr=0.3,0.1

Type RM Length L Ch R = 1 ,16849.6 ,260.9,254,246.8
XS GIS Cut Line= 2
     1673493.459      559926.733     1674091.258      559978.614
#Sta/Elev= 30
       0  633.61     9.8  632.64    49.2  627.29   108.2  619.58   137.7  615.48
   177.1  609.43   186.9  608.12   196.7  607.16   226.2  605.17   245.9  603.96
   285.3  602.09   328.6600.6086   344.3  599.94   354.1   600.1   363.6601.9329
   373.8  605.45   383.6  609.14   393.5  612.33     423  621.39   432.8  624.86
   442.7  628.85   452.5  633.12   462.3  637.71   472.2  642.77     482  648.12
   491.8   653.3   511.5  662.84     541  676.32   570.5  689.39     600  702.32
#Mann= 3 , 0 , 0
       0     .06       0   328.6    .045       0   363.6      .1       0
Bank Sta=328.6,363.6
XS Rating Curve= 0 ,0
Exp/Cntr=0.3,0.1

Type RM Length L Ch R = 1 ,16595.6 ,202.2,200.8,198.8
XS GIS Cut Line= 2
      1673522.75       560263.92     1674125.119      560125.755
#Sta/Elev= 30
       0  648.43    39.2  634.92      49  631.92    58.9  630.09    68.7  629.06
    78.5   627.5   107.9  620.24   127.5  615.94   147.2  612.08   176.6  606.83
   186.4  605.29     206  602.74   215.8  601.72   235.4  600.22     255   599.3
   299.1598.4467   313.9  598.29   323.7  598.54   334.1 599.538   343.3  601.04
   353.2  603.08     363  605.46     412  619.16   421.8  622.15   431.6  625.61
   451.2  633.16   490.5  647.68   510.1   655.3   578.8  682.97     618  697.62
#Mann= 3 , 0 , 0
       0     .06       0   299.1    .045       0   334.1      .1       0
Bank Sta=299.1,334.1
XS Rating Curve= 0 ,0
Exp/Cntr=0.3,0.1

Type RM Length L Ch R = 1 ,16394.8 ,225.7,233.3,240.7
XS GIS Cut Line= 2
     1673527.109      560476.625     1674151.288      560290.017
#Sta/Elev= 30
       0  663.83    97.2  633.55     107  630.67   116.7  628.55   136.1  626.14
   145.8  623.99   165.3  618.58   204.2     607   213.9  604.43   223.6   602.4
   233.4  600.92   243.1   599.8   252.8  598.77   272.3  597.19   291.7  596.16
   301.4  595.87   340.3  595.39   359.8  595.61   388.9  596.44   401.6596.4092
   418.1  596.34   427.8  597.83   436.6600.6406   447.3  604.14   505.6  619.82
   515.4  622.61   525.1  625.74   534.8   629.4   593.1  653.59   651.5  676.85
#Mann= 3 , 0 , 0
       0     .06       0   401.6    .045       0   436.6      .1       0
Bank Sta=401.6,436.6
XS Rating Curve= 0 ,0
Exp/Cntr=0.3,0.1

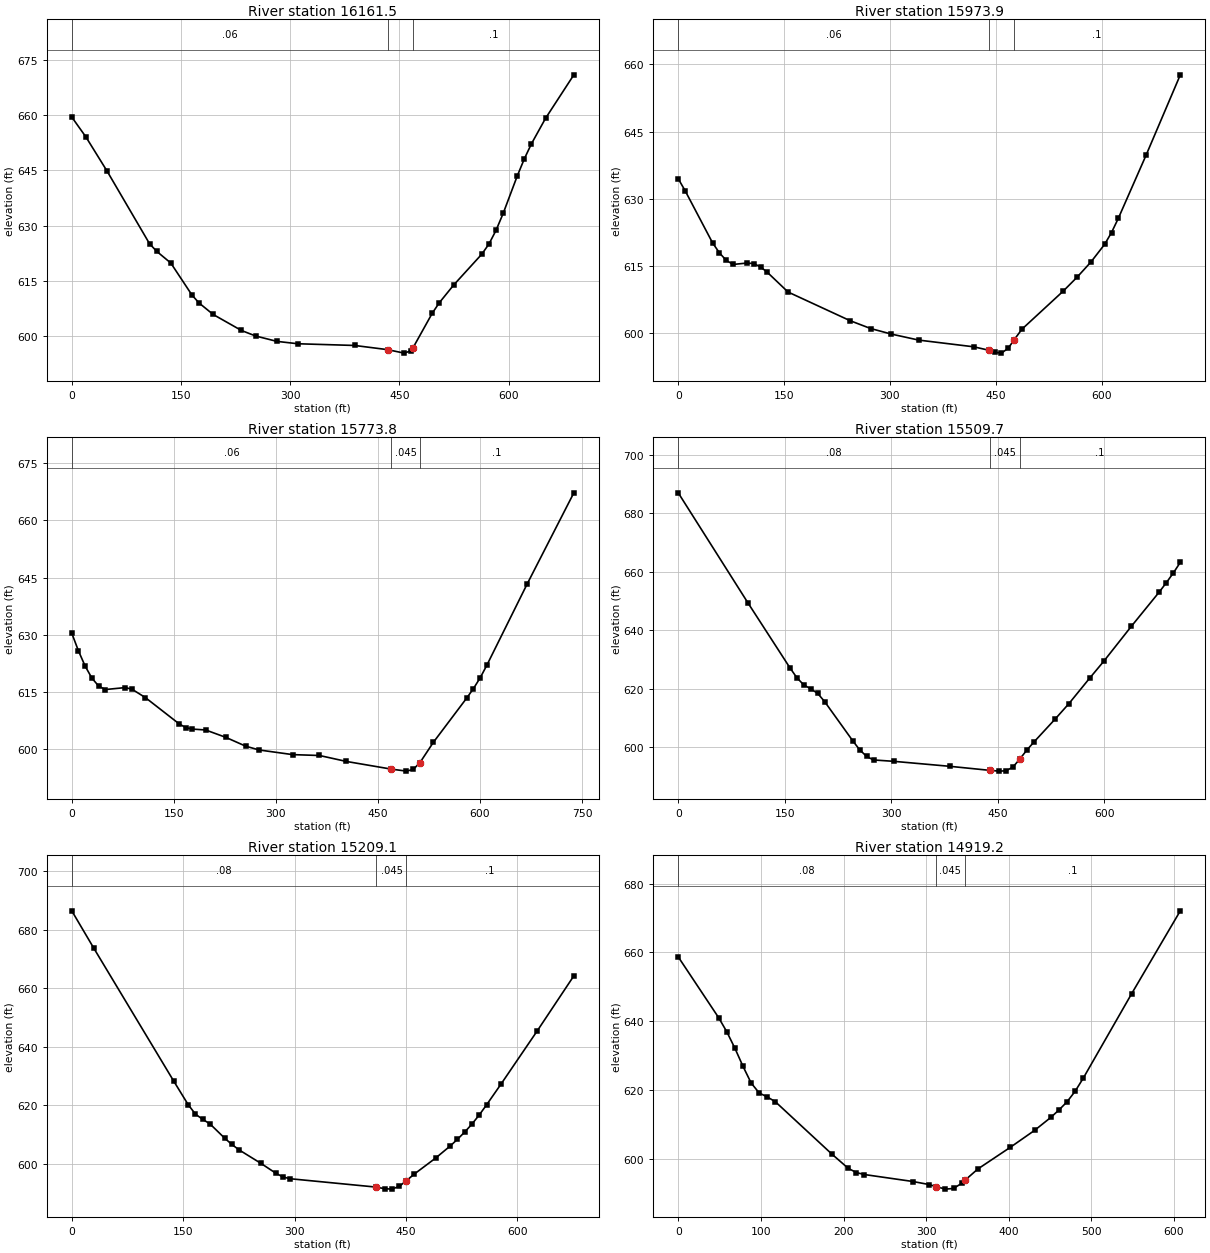
Type RM Length L Ch R = 1 ,16161.5 ,187,187.6,188.1
XS GIS Cut Line= 2
     1673549.825      560553.871     1674238.695      560585.153
#Sta/Elev= 30
       0  659.49    19.4   654.1    48.6  644.79   106.8  625.13   116.6  623.07
     136  619.89   165.1   611.2   174.8  609.05   194.2  605.93   233.1  601.58
   252.5  600.09   281.7  598.63   310.8  597.98   388.5  597.52   433.9596.3821
   456.5  595.44   466.2  596.09   468.9596.9585   495.3  606.33     505  609.16
   524.5  613.91   563.3  622.32     573  625.05   582.7  628.75   592.5  633.34
   611.9  643.52   621.6  648.16   631.3  652.22   650.7  659.14   689.6  670.95
#Mann= 3 , 0 , 0
       0     .06       0   433.9    .045       0   468.9      .1       0
Bank Sta=433.9,468.9
XS Rating Curve= 0 ,0
Exp/Cntr=0.3,0.1

Type RM Length L Ch R = 1 ,15973.9 ,206.4,200,193.5
XS GIS Cut Line= 3
     1673576.248      560626.671     1673686.005      560736.976
     1674240.538      560776.353
#Sta/Elev= 30
       0  634.45     9.7   631.8    48.6  620.14    58.4  617.88    68.1  616.21
    77.8   615.3    97.2  615.61     107   615.5   116.7  614.74   126.4  613.52
   155.6  609.14   243.4  602.74   272.6  600.98   301.9  599.74   340.9  598.39
   418.9  596.89   440.4596.1177   448.2  595.68     458  595.48   467.7  596.58
   475.4  598.34   487.2  600.85   545.7  609.36   565.2  612.45   584.8  615.84
   604.2  619.78     614  622.43   623.8  625.66   662.8  639.65   711.5  657.68
#Mann= 3 , 0 , 0
       0     .06       0   440.4    .045       0   475.4      .1       0
Bank Sta=440.4,475.4
XS Rating Curve= 0 ,0
Exp/Cntr=0.3,0.1

Type RM Length L Ch R = 1 ,15773.8 ,270.3,264.1,257.7
XS GIS Cut Line= 2
     1673570.601      561044.249     1674292.742      560891.891
#Sta/Elev= 30
       0  630.36     9.8  625.72    19.7  621.69    29.5  618.57    39.4  616.48
    49.2  615.54    78.7  616.06    88.6  615.62   108.2  613.43   157.4  606.58
   167.3  605.54   177.1  605.15   196.8  604.91   226.3  602.98   255.8  600.64
   275.5  599.65   324.7  598.43   364.1   598.2   403.5  596.64   469.9594.6108
     492  594.09   501.9  594.54   511.7   596.3   531.4  601.64   580.6  613.32
   590.4  615.79   600.3  618.62   610.1  621.93   669.2  643.24     738  667.27
#Mann= 3 , 0 , 0
       0     .06       0   469.9    .045       0   511.7      .1       0
Bank Sta=469.9,511.7
XS Rating Curve= 0 ,0
Exp/Cntr=0.3,0.1

Type RM Length L Ch R = 1 ,15509.7 ,294.9,300.6,306.2
XS GIS Cut Line= 2
     1673765.522      561390.988     1674390.473      561060.217
#Sta/Elev= 30
       0  686.94    98.2  649.34   157.1  627.26     167  623.82   176.8  621.34
   186.6  620.01   196.4  618.44   206.2  615.64   245.5  602.35   255.3  599.25
   265.2  596.94     275  595.72   304.4  595.23     383  593.53   439.4592.1489
   451.8   591.9   461.6     592   471.4  593.28   481.2  596.08     491   599.1
   500.8   601.8   530.3  609.54     550  614.89   579.4  623.64   599.1  629.36
   638.3   641.4   677.6  653.12   687.4  656.25   697.3  659.58   707.1   663.2
#Mann= 3 , 0 , 0
       0     .08       0   439.4    .045       0   481.2      .1       0
Bank Sta=439.4,481.2
XS Rating Curve= 0 ,0
Exp/Cntr=0.3,0.1

Type RM Length L Ch R = 1 ,15209.1 ,289.4,289.9,290.3
XS GIS Cut Line= 2
     1673881.369       561546.52     1674538.216      561387.148
#Sta/Elev= 30
       0  686.48    29.4   673.8   137.1  628.27   156.7  620.15   166.5   616.9
   176.3  615.12   186.1  613.55   205.7  608.71   215.5  606.53   225.3  604.66
   254.7  600.05   274.3  596.75   284.1  595.42   293.9   594.8   410.1591.9251
   421.2  591.39     431  591.24   440.8  592.18   450.6  594.15   460.4  596.26
   489.8  601.86   509.4  605.99   519.2  608.29     529  610.78   538.8  613.52
   548.6  616.64   558.4  620.08     578  627.24   626.9   645.5   675.9  664.23
#Mann= 3 , 0 , 0
       0     .08       0   410.1    .045       0   450.6      .1       0
Bank Sta=410.1,450.6
XS Rating Curve= 0 ,0
Exp/Cntr=0.3,0.1

Type RM Length L Ch R = 1 ,14919.2 ,302.5,296.7,290.1
XS GIS Cut Line= 2
     1674059.915      561797.646     1674650.335      561654.392
#Sta/Elev= 30
       0   658.7      49  640.99    58.8  636.91    68.6  632.12    78.4  626.86
    88.2  622.04      98  619.12   107.8  617.97   117.6  616.56   186.2  601.29
   205.8   597.2   215.6  595.97   225.4   595.4   284.2  593.37   303.8  592.48
   311.7591.9157   323.4  591.16   333.2  591.36     343  592.85   346.7593.6768
   362.6  597.02   401.8  603.31   431.2  608.24   450.8     612   460.6  614.15
   470.4  616.52   480.2  619.58     490  623.37   548.8  648.04   607.6   672.1
#Mann= 3 , 0 , 0
       0     .08       0   311.7    .045       0   346.7      .1       0
Bank Sta=311.7,346.7
XS Rating Curve= 0 ,0
Exp/Cntr=0.3,0.1

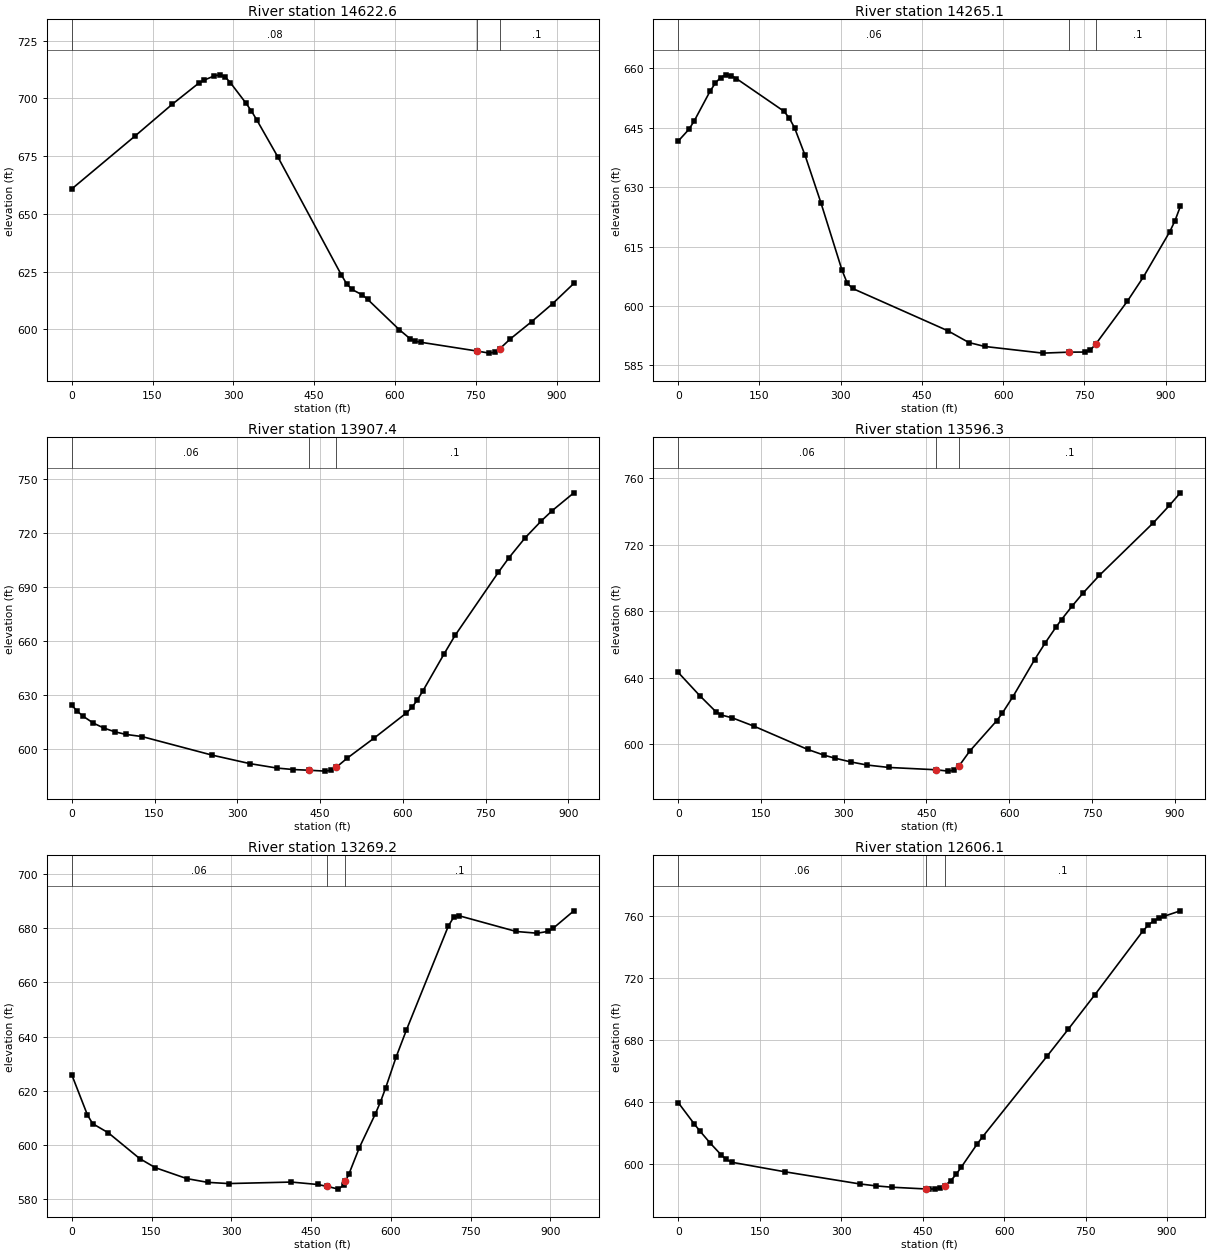
Type RM Length L Ch R = 1 ,14622.6 ,372.7,357.5,342.6
XS GIS Cut Line= 2
     1673809.296      562341.963     1674631.576      561903.277
#Sta/Elev= 30
       0   660.8   117.7  683.76   186.4  697.44   235.4  706.54   245.3  707.86
   264.9  709.79   274.7   710.2   284.5  709.38   294.3  706.82   323.7  697.83
   333.6  694.49   343.4  690.69   382.6  674.63   500.3  623.64   510.1  619.78
     520   617.3   539.6  614.89   549.4  612.96   608.2  599.82   627.9  595.98
   637.7  594.88   647.5  594.44     753590.5955     775  589.72   784.8  590.12
   794.6  591.62   814.3  595.92   853.5  603.32   892.7  611.16     932   619.9
#Mann= 3 , 0 , 0
       0     .08       0     753    .045       0   794.6      .1       0
Bank Sta=753,794.6
XS Rating Curve= 0 ,0
Exp/Cntr=0.3,0.1

Type RM Length L Ch R = 1 ,14265.1 ,368.6,357.7,346.7
XS GIS Cut Line= 2
     1674409.919        562935.9     1674783.932      562087.628
#Sta/Elev= 30
       0  641.61    19.5  644.53    29.3  646.63    58.6  654.14    68.3  656.19
    78.1  657.64    87.8  658.32    97.6  658.14   107.3  657.38   195.2  649.13
   204.9  647.44   214.7  644.99   234.2  638.01   263.5  626.03   302.5     609
   312.3  605.69     322  604.42   497.7  593.76   536.7  590.78     566  589.79
   673.3  588.11   722.1  588.36   751.4  588.38   761.2  588.92   770.9  590.38
   829.5  601.24   858.8   607.3   907.6  618.73   917.3  621.53   927.1  625.11
#Mann= 3 , 0 , 0
       0     .06       0   722.1    .045       0   770.9      .1       0
Bank Sta=722.1,770.9
XS Rating Curve= 0 ,0
Exp/Cntr=0.3,0.1

Type RM Length L Ch R = 1 ,13907.4 ,316.5,311.1,305.6
XS GIS Cut Line= 2
     1675058.408      562860.783     1674997.547      561952.737
#Sta/Elev= 30
       0  624.13     9.8  620.94    19.6  618.28    39.1  614.24    58.7  611.43
    78.3   609.4    97.9  607.97   127.2  606.77   254.4  596.44   322.9  591.71
   371.9  589.25   401.2  588.43   429.9588.0322   459.9  587.54   469.7  588.05
   479.5  589.69   499.1  594.71     548   605.9   606.7  619.92   616.5  622.96
   626.3   627.1   636.1  631.96   675.2   652.9   694.8  663.02   773.1  698.04
   792.6  706.27     822  717.37   851.4  726.79   870.9  732.41   910.1  742.32
#Mann= 3 , 0 , 0
       0     .06       0   429.9    .045       0   479.5      .1       0
Bank Sta=429.9,479.5
XS Rating Curve= 0 ,0
Exp/Cntr=0.3,0.1

Type RM Length L Ch R = 1 ,13596.3 ,326.2,327.1,327.8
XS GIS Cut Line= 2
     1675469.903      562788.294      1675193.85      561921.088
#Sta/Elev= 30
       0  643.11    39.1   629.1    68.5  619.38    78.3  617.46    97.9  615.77
     137  610.78   234.9  596.71   264.2   593.3   283.8  591.49   313.2  589.18
   342.5  587.33   381.6  585.89   467.7 584.483   489.3  583.67   499.1  584.14
   508.9  586.75   528.4  595.72   577.4  614.06   587.2  618.46   606.7  628.53
   645.9  650.76   665.4     661     685  670.54   694.8  674.99   714.4  683.24
   733.9  690.96   763.3  701.55   861.2  733.24   890.5  743.75   910.1   751.3
#Mann= 3 , 0 , 0
       0     .06       0   467.7    .045       0   508.9      .1       0
Bank Sta=467.7,508.9
XS Rating Curve= 0 ,0
Exp/Cntr=0.3,0.1

Type RM Length L Ch R = 1 ,13269.2 ,640.2,663.1,678
XS GIS Cut Line= 2
     1675759.659      562649.426     1675450.531       561757.47
#Sta/Elev= 30
       0  625.91    29.5   611.1    39.3  607.91    68.8  604.53   127.8  595.04
   157.3  591.69   216.3  587.68   255.7   586.3     295  585.86     413  586.41
   462.2  585.52   479.5584.8474   501.5  583.81   511.3  585.34   514.5586.6588
   521.2  589.42   540.8  599.12   570.3  611.31   580.2  615.82     590  620.99
   609.7  632.37   629.3  642.44     708  680.64   717.8  683.86   727.7  684.48
   835.8  678.66   875.2  678.03   894.8  678.68   904.7  679.78     944  686.27
#Mann= 3 , 0 , 0
       0     .06       0   479.5    .045       0   514.5      .1       0
Bank Sta=479.5,514.5
XS Rating Curve= 0 ,0
Exp/Cntr=0.3,0.1

Type RM Length L Ch R = 1 ,12606.1 ,414.6,412.6,416.2
XS GIS Cut Line= 2
     1675856.428      562662.127     1676228.119      561815.725
#Sta/Elev= 30
       0  639.44    29.5  625.65    39.3  621.34      59  613.22    78.7   605.8
    88.5  602.71    98.3  600.92   196.7  594.72   334.4  586.89   363.9  585.65
   393.4  584.77   455.9583.6428   462.2  583.54     472  583.69   481.9  584.37
   490.9585.8302   501.6   588.9   511.4     593   521.2  597.79   550.7  612.86
   560.6  617.46   678.6  669.24   717.9  686.77   767.1  709.14   855.6  750.35
   865.4  754.11   875.2  756.85   885.1  758.57   894.9  759.88   924.4  763.36
#Mann= 3 , 0 , 0
       0     .06       0   455.9    .045       0   490.9      .1       0
Bank Sta=455.9,490.9
XS Rating Curve= 0 ,0
Exp/Cntr=0.3,0.1

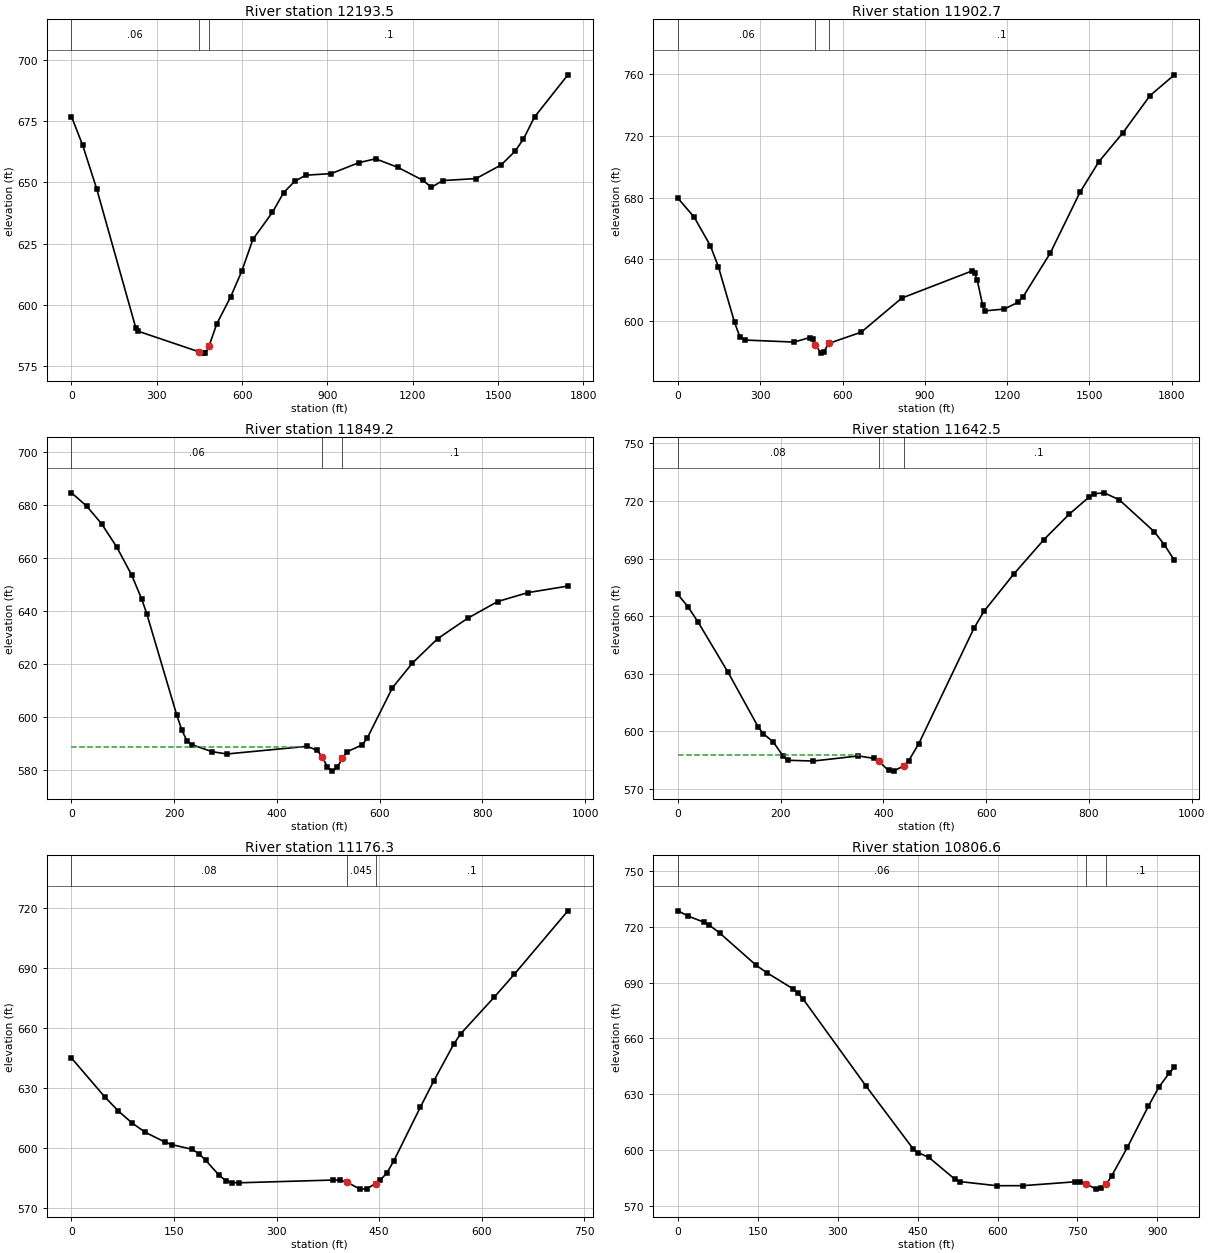
Type RM Length L Ch R = 1 ,12193.5 ,275.1,290.8,303.1
XS GIS Cut Line= 3
     1676136.831       562783.08     1676662.655       562036.75
     1677142.354      561355.885
#Sta/Elev= 30
       0  676.89    39.3  665.21    88.4  647.48   225.8   590.8   235.6  589.26
   448.5580.9087   461.4  580.37   471.2  580.41   483.5583.1578   510.5  592.19
   559.6  603.31   598.8   613.8   638.1  626.82   706.8  637.84   746.1  645.86
   785.3  650.53   824.6  652.99     913  653.61    1011  658.11  1069.7  659.66
  1148.1  656.16  1236.3  650.86  1265.7     648  1304.9  650.77  1422.5  651.59
  1510.7  657.13  1559.7  662.74  1589.1  667.67  1628.3  676.71  1745.8  693.93
#Mann= 3 , 0 , 0
       0     .06       0   448.5    .045       0   483.5      .1       0
Bank Sta=448.5,483.5
XS Rating Curve= 0 ,0
Exp/Cntr=0.3,0.1

Type RM Length L Ch R = 1 ,11902.7 ,53.1,53.5,53.8
XS GIS Cut Line= 3
     1676184.396      562794.732     1677006.036      562330.773
     1677760.119       561904.96
#Sta/Elev= 30
       0  679.54      59  667.37     118  648.94   147.4  635.28   206.4  599.29
   226.1  589.76   245.7  587.89   422.6  586.59   481.6  589.54   491.4  588.66
   501.3  584.87   520.9  579.44   530.8  580.16   550.4  585.75   668.4  593.01
   815.8  615.01  1071.5  632.53  1081.4  631.29  1091.2  626.44  1110.9  610.27
  1120.7  606.77  1189.6  607.94  1238.8  612.21  1258.5  615.98  1356.9  644.02
  1465.2  683.31    1534  703.11  1622.6  722.04    1721  745.94  1809.6  759.33
#Mann= 3 , 0 , 0
       0     .06       0   501.3    .045       0   550.4      .1       0
Bank Sta=501.3,550.4
XS Rating Curve= 0 ,0
Exp/Cntr=0.3,0.1

Type RM Length L Ch R = 1 ,11849.2 ,202,206.7,211.3
XS GIS Cut Line= 2
     1676214.229      562825.392     1677066.156      562369.082
#Sta/Elev= 30
       0   684.6    29.3  679.66    58.6  672.93    87.9  664.23   117.1  653.62
   136.7  644.54   146.4   639.1     205  600.75   214.8  595.16   224.5  591.15
   234.3  589.65   273.3  587.02   302.6  586.14   458.8  589.02   478.3   587.5
   488.3585.0319   497.9  581.28   507.6  579.67   517.4  581.12   527.2  584.48
   536.9  587.01   566.2   589.6     576  592.24   624.8   611.1   663.8  620.44
   712.6  629.58   771.2   637.3   829.8  643.62   888.3  646.97   966.4  649.44
#Mann= 3 , 0 , 0
       0     .06       0   488.3    .045       0   527.2      .1       0
#XS Ineff= 2 , 0
          449.07  588.93
Permanent Ineff=
       F       F
Bank Sta=488.3,527.2
XS Rating Curve= 0 ,0
Exp/Cntr=0.3,0.1

Type RM Length L Ch R = 1 ,11642.5 ,451.4,466.2,480.8
XS GIS Cut Line= 2
     1676311.886      562903.077      1677232.94      562610.404
#Sta/Elev= 30
       0  671.32    19.5  664.94      39  657.03    97.6  630.76   156.2  602.32
     166  598.78   185.5  594.58     205  586.93   214.8  584.96   263.6  584.57
   351.4  587.22   380.7  585.97   390.5  584.55     410  579.65   419.8  579.31
   439.3  582.04     449  584.66   468.6  593.48     576  653.62   595.5  662.49
     654  682.04   712.6  699.96   761.4  713.09   800.5  722.11   810.2  723.79
   829.8  724.28     859  720.66   927.4  703.99   946.9  697.22   966.4  689.13
#Mann= 3 , 0 , 0
       0     .08       0   390.5    .045       0   439.3      .1       0
#XS Ineff= 2 , 0
          352.52  587.55
Permanent Ineff=
       F       F
Bank Sta=390.5,439.3
XS Rating Curve= 0 ,0
Exp/Cntr=0.3,0.1

Type RM Length L Ch R = 1 ,11176.3 ,369.6,369.7,369.8
XS GIS Cut Line= 2
     1676233.812       563044.95      1676911.48      563305.678
#Sta/Elev= 30
       0  645.15    49.1  625.58    68.7  618.66    88.3  612.78   107.9  608.05
   137.4  603.05   147.2  601.85   176.6  599.55   186.4  597.32   196.2  594.09
   215.9  586.59   225.7   583.9   235.5  582.92   245.3  582.82   382.7  584.19
   392.5  584.13   402.3  583.24   421.9  579.65   431.7  579.86   445.1582.4491
   451.4  584.04   461.2  587.74     471  593.46   510.2  620.56   529.8  633.64
   559.3  652.22   569.1  657.21   618.2  675.54   647.6  686.99   726.1  718.73
#Mann= 3 , 0 , 0
       0     .08       0   402.3    .045       0   445.1      .1       0
Bank Sta=402.3,445.1
XS Rating Curve= 0 ,0
Exp/Cntr=0.3,0.1

Type RM Length L Ch R = 1 ,10806.6 ,295.6,262.6,229.6
XS GIS Cut Line= 2
     1675788.458      563251.656     1676658.314      563586.328
#Sta/Elev= 30
       0  728.46    19.6  725.57      49  722.36    58.9   720.8    78.5  716.52
   147.2  699.16   166.8  695.28   215.8  686.66   225.6  684.22   235.5  680.93
   353.2   634.4   441.5  600.78   451.3  598.66   470.9   596.2     520  584.46
   529.8  583.18   598.4  580.98   647.5  581.01   745.6  583.08   755.4  583.08
   765.2  582.13   784.9  579.15   794.7  579.49   804.4581.8655   814.3  586.27
   843.7  601.53     883  623.57   902.6  633.72   922.2  641.37     932  644.52
#Mann= 3 , 0 , 0
       0     .06       0   765.2    .045       0   804.4      .1       0
Bank Sta=765.2,804.4
XS Rating Curve= 0 ,0
Exp/Cntr=0.3,0.1

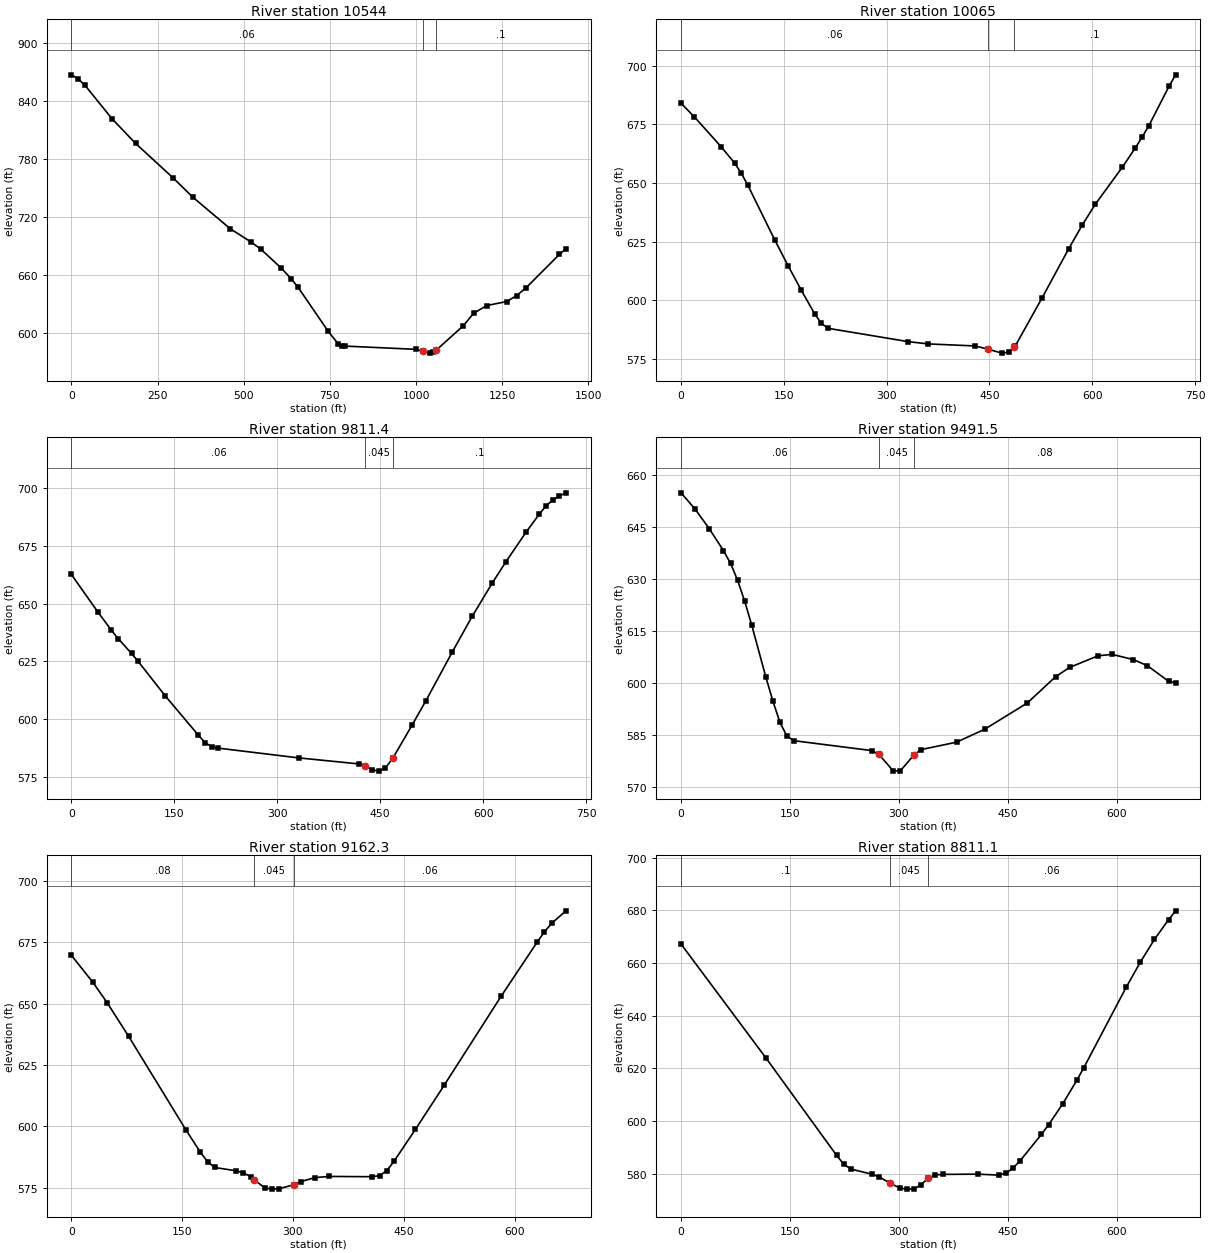
Type RM Length L Ch R = 1 ,10544   ,466.8,479,491.3
XS GIS Cut Line= 3
     1676094.419      564674.178     1676663.291      563655.262
     1676930.047      563680.071
#Sta/Elev= 30
       0  867.44    19.6  863.31    39.2  856.68   117.7  821.94   186.3  796.28
   294.2  760.79     353   740.3   460.9  707.76   519.7  694.36   549.2  686.67
     608  667.27   637.4  656.03     657  647.37   745.3  601.21   774.7  588.07
   784.5  586.32   794.3  586.02  1000.2  582.66  1019.9   580.6  1039.5  578.73
  1049.3  579.44  1057.6 581.515  1137.5  607.28    1167   620.1  1205.2  628.12
  1262.6   632.2  1291.4  638.29    1320   646.8  1415.7  681.07  1434.9     687
#Mann= 3 , 0 , 0
       0     .06       0  1019.9    .045       0  1057.6      .1       0
Bank Sta=1019.9,1057.6
XS Rating Curve= 0 ,0
Exp/Cntr=0.3,0.1

Type RM Length L Ch R = 1 ,10065   ,249.7,253.5,257.3
XS GIS Cut Line= 2
     1676568.699      564273.564     1677189.159      563905.233
#Sta/Elev= 30
       0  683.97    19.5  678.14    58.5  665.44      78  658.58    87.8  654.19
    97.5  649.03   136.5  625.86     156  614.86   175.5   604.3     195  594.22
   204.8  590.22   214.5  588.11   331.5  582.43   360.8  581.46     429   580.6
   448.5  579.19     468  577.54   477.8  577.89   486.4580.2307   487.5  580.53
   526.5  600.94   565.5  621.94     585  631.94   604.5     641   643.6  656.65
     663  665.04   672.8  669.61   682.6  674.45   711.8  691.12   721.6  696.09
#Mann= 3 , 0 , 0
       0     .06       0   448.5    .045       0   486.4      .1       0
Bank Sta=448.5,486.4
XS Rating Curve= 0 ,0
Exp/Cntr=0.3,0.1

Type RM Length L Ch R = 1 ,9811.4  ,320,319.9,319
XS GIS Cut Line= 2
     1676656.447       564423.66     1677329.338      564165.622
#Sta/Elev= 30
       0  662.63      39  646.22    58.4  638.43    68.2  634.86    87.6  628.42
    97.4  624.96   136.3  610.22     185  593.05   194.8  589.86   204.5     588
   214.2  587.42   331.1  583.21   418.8   580.6   428.5  579.54   438.2  578.04
     448  577.47   457.7  578.87   468.3583.0291   496.7  597.52   516.2  607.75
   555.1  629.08   584.3  644.64   613.5     659     633  668.06   662.2  680.82
   681.7  688.71   691.4  692.25   701.2  694.83   710.9  696.64   720.7     698
#Mann= 3 , 0 , 0
       0     .06       0   428.5    .045       0   468.3      .1       0
Bank Sta=428.5,468.3
XS Rating Curve= 0 ,0
Exp/Cntr=0.3,0.1

Type RM Length L Ch R = 1 ,9491.5  ,303.9,329.2,377.2
XS GIS Cut Line= 2
     1676841.061       564683.53      1677476.89      564439.704
#Sta/Elev= 30
       0  654.89    19.5  650.14    38.9  644.51    58.4   638.2    68.1  634.54
    77.8  629.68    87.6  623.59    97.3  616.71   116.7  601.74   126.5  594.72
   136.2   588.6   145.9  584.62   155.6  583.33   262.7  580.48   272.4  579.37
   291.8   574.7   301.6  574.55     321  579.29   330.8  580.78   379.4  582.91
   418.3  586.67   476.7  594.21   515.6  601.79     535  604.49     574  607.83
   593.4  608.26   622.6  606.76   642.1     605   671.2  600.49     681  600.03
#Mann= 3 , 0 , 0
       0     .06       0   272.4    .045       0     321     .08       0
Bank Sta=272.4,321
XS Rating Curve= 0 ,0
Exp/Cntr=0.3,0.1

Type RM Length L Ch R = 1 ,9162.3  ,359.8,351.2,318.8
XS GIS Cut Line= 2
     1676786.513      564699.346     1677347.932      565064.348
#Sta/Elev= 30
       0  669.71    29.1   658.7    48.5  650.36    77.6  636.64   155.3  598.42
   174.7  589.39   184.4  585.56   194.1  583.21   223.2  581.86   232.9  581.02
   242.6  579.46   247.5578.1466     262   574.9   271.7  574.39   281.4  574.57
   300.8  576.14   310.6  577.45     330  579.11   349.4  579.56   407.6  579.45
   417.3  579.91     427  581.92   436.7  585.71   465.8  598.75   504.7  616.73
   582.3  653.26   630.8  675.18   640.5  679.29   650.2  682.76   669.6  687.86
#Mann= 3 , 0 , 0
       0     .08       0   247.5    .045       0   300.8     .06       0
Bank Sta=247.5,300.8
XS Rating Curve= 0 ,0
Exp/Cntr=0.3,0.1

Type RM Length L Ch R = 1 ,8811.1  ,279.6,271.8,263.5
XS GIS Cut Line= 2
     1676590.092      564915.057     1677206.898      565204.234
#Sta/Elev= 30
       0   667.2   116.8  623.98   214.1  586.97   223.8  583.66   233.6  581.74
   262.8  579.78   272.5  578.81   287.8576.3729   301.7  574.48   311.4   574.1
   321.2  574.17   330.9  575.84   340.6   578.3   350.4  579.48   360.1   579.7
   408.7  579.79   437.9  579.42   447.7  580.17   457.4  582.14   467.1  584.91
   496.3  594.88   506.1  598.51   525.5  606.45     545  615.39   554.7  620.22
   613.1  650.79   632.6  660.35     652  668.98   671.5  676.48   681.2  679.84
#Mann= 3 , 0 , 0
       0      .1       0   287.8    .045       0   340.6     .06       0
Bank Sta=287.8,340.6
XS Rating Curve= 0 ,0
Exp/Cntr=0.3,0.1

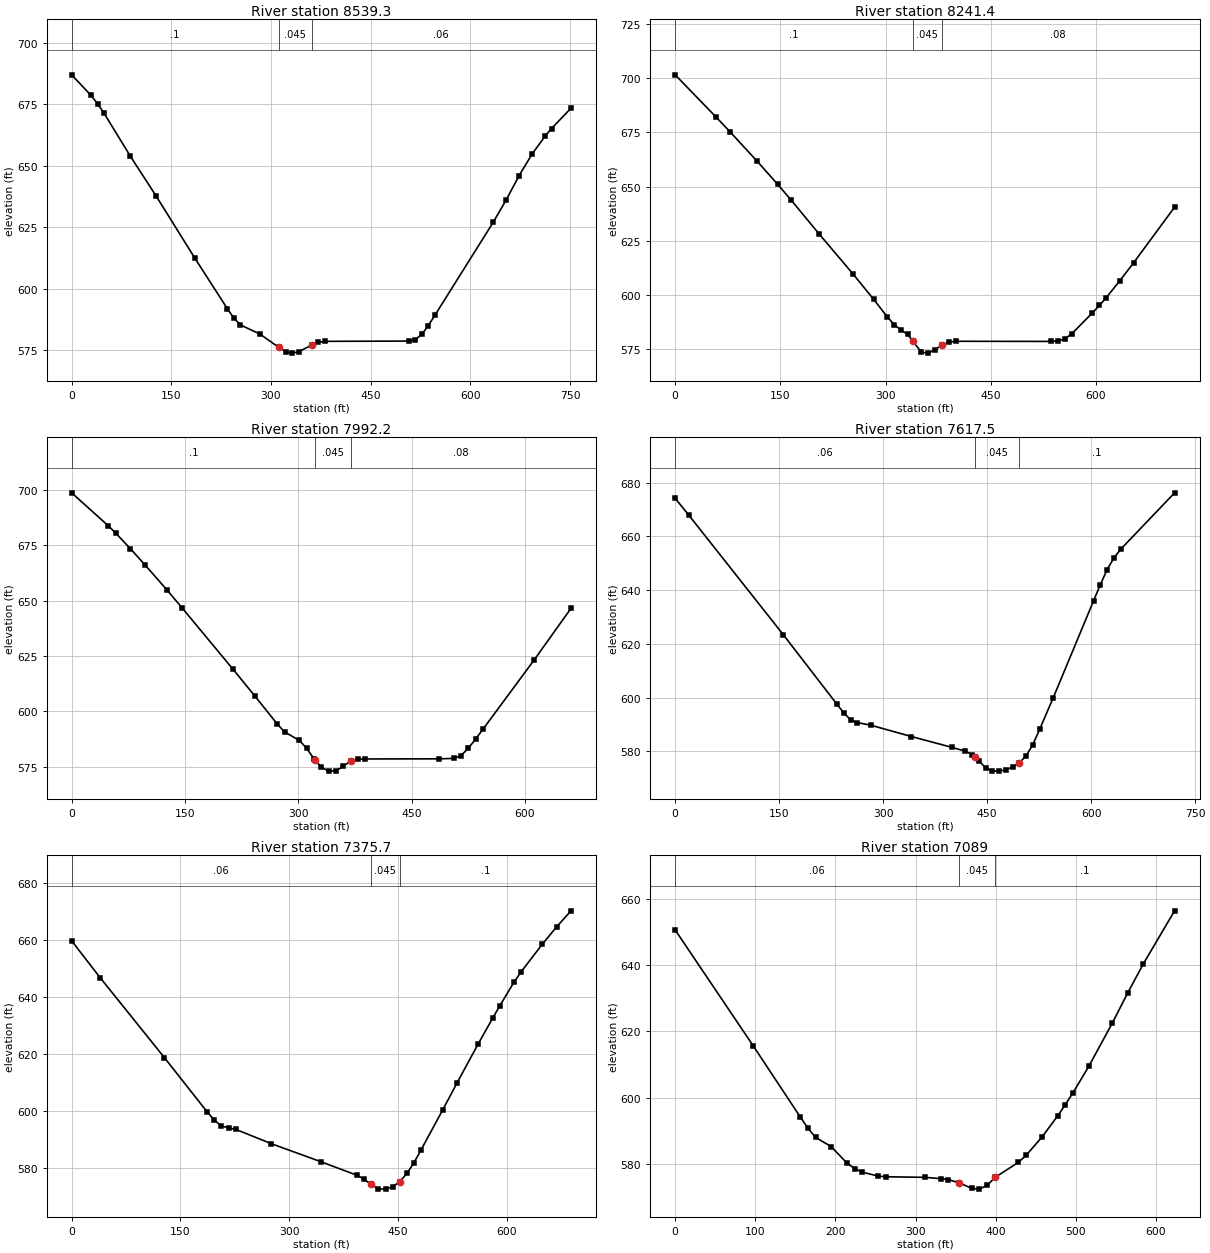
Type RM Length L Ch R = 1 ,8539.3  ,310,297.9,286.7
XS GIS Cut Line= 2
     1676424.376      565258.248     1677175.798       565272.39
#Sta/Elev= 30
       0   686.9    29.3  678.53      39  675.18    48.8  671.31    87.8   654.1
   126.9  637.79   185.4  612.48   234.2  591.99     244  588.17   253.8  585.36
     283  581.71   311.5576.2766   322.1  574.45   331.9  573.89   341.6  574.45
   361.1  577.12   370.9  578.24   380.7  578.68   507.5  578.78   517.3  579.42
   527.1   581.5   536.8  585.09   546.6  589.23   634.4  626.99     654  636.13
   673.5     646     693  654.74   712.5  661.97   722.3   665.1   751.6  673.37
#Mann= 3 , 0 , 0
       0      .1       0   311.5    .045       0   361.1     .06       0
Bank Sta=311.5,361.1
XS Rating Curve= 0 ,0
Exp/Cntr=0.3,0.1

Type RM Length L Ch R = 1 ,8241.4  ,259.2,249.2,239.2
XS GIS Cut Line= 2
     1676490.972      565688.752     1677117.443      565349.695
#Sta/Elev= 30
       0  701.61    58.6  682.01    78.1  675.34   117.1  661.64   146.4  650.95
   165.9  643.56   204.9  628.25   253.7   609.6     283  597.93   302.5  589.83
   312.3  586.23     322  583.74   331.8  581.66   338.6578.6666   351.3  573.47
     361  573.05   370.8  574.67   380.6  576.78   390.3  578.12   400.1  578.52
   536.7  578.46   546.4  578.67   556.2  579.68     566   582.1   595.2  591.67
     605  595.06   614.8  598.66   634.3  606.52   653.8  614.75   712.3  640.48
#Mann= 3 , 0 , 0
       0      .1       0   338.6    .045       0   380.6     .08       0
Bank Sta=338.6,380.6
XS Rating Curve= 0 ,0
Exp/Cntr=0.3,0.1

Type RM Length L Ch R = 1 ,7992.2  ,373.1,374.6,371.1
XS GIS Cut Line= 2
     1676805.845      565928.988      1677199.64      565398.235
#Sta/Elev= 30
       0  698.62    48.6  683.72    58.3  680.44    77.8   673.4    97.2  666.04
   126.4  654.69   145.8  646.84   213.8   618.9     243   606.7   272.1  594.28
   281.8   590.7   301.3  586.88     311  583.32   320.7  578.57   322.5 577.863
   330.4  574.76   340.2  573.01   349.9  573.23   359.6  575.14   369.3  577.64
     379  578.39   388.8   578.5     486  578.56   505.4  578.75   515.1     580
   524.8  583.24   534.5  587.44   544.3  591.91   612.3  623.29   660.9  646.51
#Mann= 3 , 0 , 0
       0      .1       0   322.5    .045       0   369.3     .08       0
Bank Sta=322.5,369.3
XS Rating Curve= 0 ,0
Exp/Cntr=0.3,0.1

Type RM Length L Ch R = 1 ,7617.5  ,241.8,241.9,246.6
XS GIS Cut Line= 2
     1677025.787      566096.796     1677482.655      565539.774
#Sta/Elev= 30
       0   674.2    19.5  667.98   155.8  623.48   233.6  597.46   243.4  594.25
   253.1  591.75   262.9   590.7   282.3  589.72   340.7  585.51   399.2  581.48
   418.6  580.06   428.4  578.78   433.1577.7141   438.1  576.58   447.8   573.8
   457.6  572.68   467.3  572.63     477  573.11   486.8   574.2   496.5  575.74
   506.2  578.32     516  582.54   525.7  588.15   545.2  599.85   603.6  636.08
   613.3  642.03   623.1  647.64   632.8  651.96   642.5  655.18   720.4  676.24
#Mann= 3 , 0 , 0
       0     .06       0   433.1    .045       0   496.5      .1       0
Bank Sta=433.1,496.5
XS Rating Curve= 0 ,0
Exp/Cntr=0.3,0.1

Type RM Length L Ch R = 1 ,7375.7  ,289.7,286.6,283.7
XS GIS Cut Line= 2
     1677201.917      566231.177     1677638.466      565698.929
#Sta/Elev= 30
       0  659.82    39.3  646.88   127.8  618.85   186.8  599.79   196.7  596.91
   206.5  594.86   216.4  594.18   226.2  593.66   275.4  588.62   344.2  582.25
   393.4  577.54   403.2  576.19     412 574.412   422.9  572.75   432.7  572.69
   442.5   573.5   452.4  575.35   462.2  578.18     472  582.03   481.9  586.58
   511.4  600.44     531  609.84   560.5  623.69   580.2  632.61     590  636.93
   609.7  645.28   619.5  648.93     649  658.68   668.7  664.78   688.4  670.34
#Mann= 3 , 0 , 0
       0     .06       0     412    .045       0   452.4      .1       0
Bank Sta=412,452.4
XS Rating Curve= 0 ,0
Exp/Cntr=0.3,0.1

Type RM Length L Ch R = 1 ,7089    ,485.4,482.3,475.8
XS GIS Cut Line= 2
     1677479.022      566421.696     1677793.521      565883.709
#Sta/Elev= 30
       0  650.58    97.4  615.62   155.8  594.27   165.5  590.82   175.3  587.97
   194.7  585.23   214.2  580.28     224   578.6   233.7   577.5   253.2  576.33
   262.9  576.12   311.6  575.95   331.1  575.56   340.8  575.28   354.7574.2686
     370  572.64   379.7  572.39   389.5  573.59   399.2  575.93   428.4  580.48
   438.2  582.65   457.6  588.07   477.1   594.4   486.8  597.86   496.6  601.52
   516.1  609.42   545.3  622.39   564.8  631.62   584.2  640.35   623.2  656.35
#Mann= 3 , 0 , 0
       0     .06       0   354.7    .045       0   399.2      .1       0
Bank Sta=354.7,399.2
XS Rating Curve= 0 ,0
Exp/Cntr=0.3,0.1