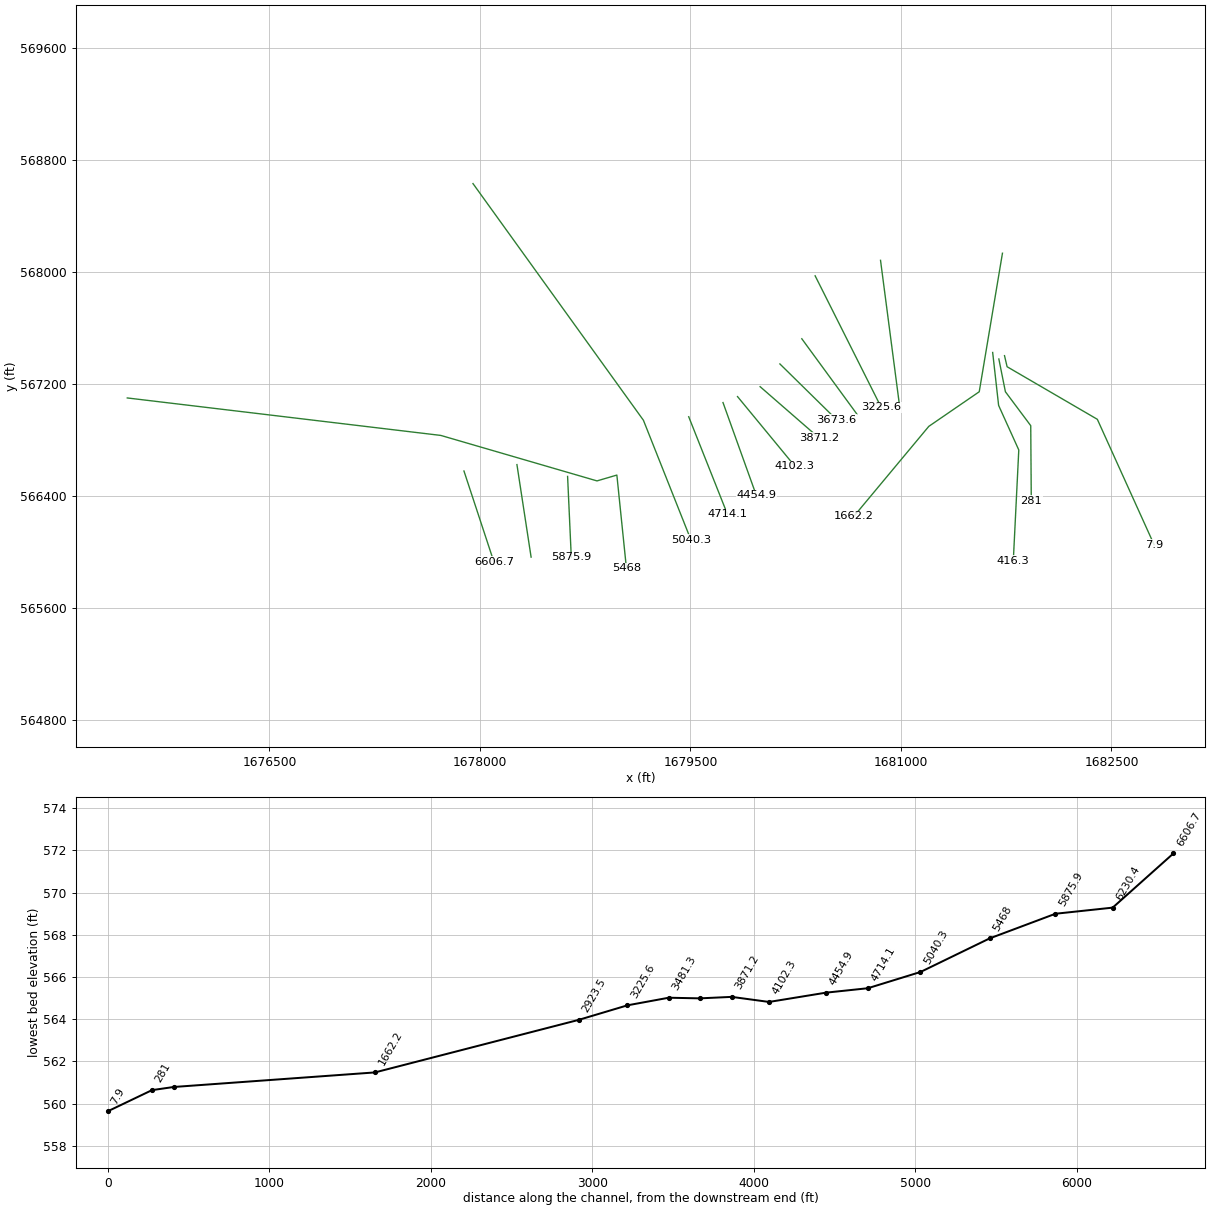
HEC-RAS study FivTwentyC.prj: FivTwentyC

--- FivTwentyC.g01 (geometry) --- (continued)

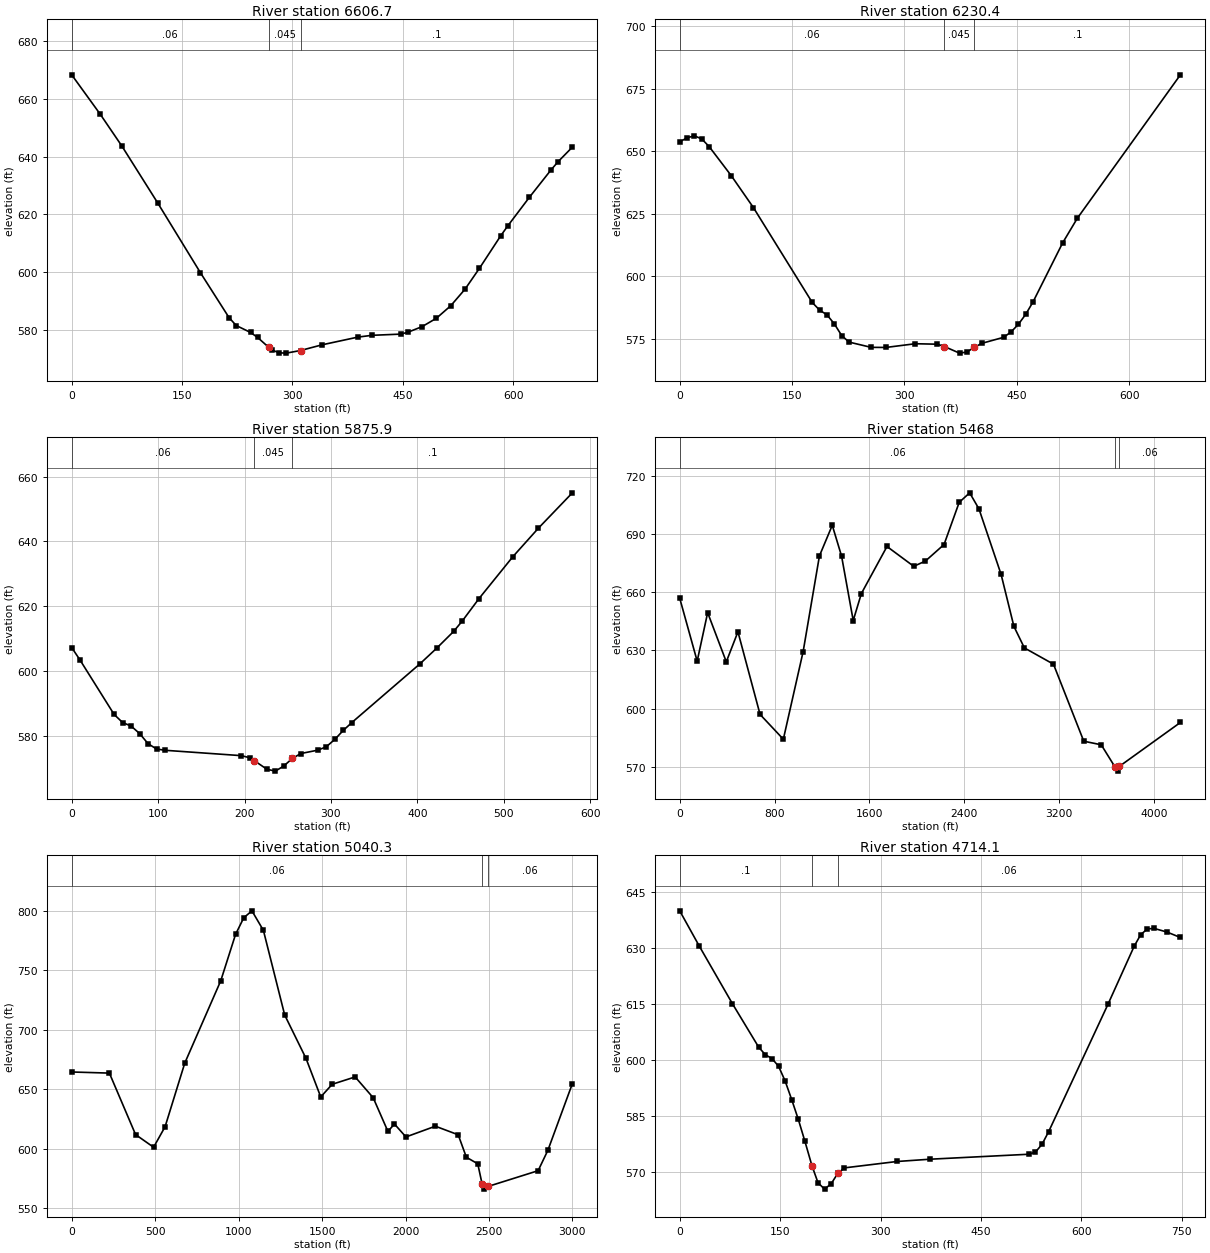
Type RM Length L Ch R = 1 ,6606.7  ,378.9,376.3,377
XS GIS Cut Line= 2
     1677885.865      566576.163     1678098.335      565929.621
#Sta/Elev= 30
       0  668.37    38.9  654.67    68.1  643.71   116.7  624.03     175  599.74
   213.9  584.17   223.6  581.44   243.1  579.03   252.8  577.28   267.6 573.918
   272.2  572.96     282  571.96   291.7  571.86   311.1  572.77   340.3  574.74
   388.9  577.41   408.3  578.04   447.2  578.45     457   579.1   476.4  581.06
   495.8  583.96   515.3   588.3   534.7  594.04   554.2  601.25   583.3  612.59
   593.1  616.09   622.2  625.91   651.4  635.34   661.1  638.23   680.6   643.3
#Mann= 3 , 0 , 0
       0     .06       0   267.6    .045       0   311.1      .1       0
Bank Sta=267.6,311.1
XS Rating Curve= 0 ,0
Exp/Cntr=0.3,0.1

Type RM Length L Ch R = 1 ,6230.4  ,357.3,354.5,350
XS GIS Cut Line= 2
     1678263.419      566621.685     1678364.358      565961.051
#Sta/Elev= 30
       0  653.79     9.8  655.44    19.7  656.23    29.5  654.96    39.3  651.92
    68.8  640.29    98.3  627.55   176.9  589.56   186.7  586.51   196.6   584.6
   206.4  580.98   216.2  576.34     226  573.71   255.5   571.6   275.2  571.56
   314.5  573.05     344  572.86   353.3571.9205   373.5  569.29   383.3  569.72
   393.1  571.57     403  573.19   432.4  575.62   442.3  577.77   452.1  580.83
   461.9  584.84   471.7  589.83     511  613.32   530.7  623.23   668.3  680.63
#Mann= 3 , 0 , 0
       0     .06       0   353.3    .045       0   393.1      .1       0
Bank Sta=353.3,393.1
XS Rating Curve= 0 ,0
Exp/Cntr=0.3,0.1

Type RM Length L Ch R = 1 ,5875.9  ,407.1,407.9,409.1
XS GIS Cut Line= 2
     1678624.412      566537.384     1678650.791      565958.532
#Sta/Elev= 30
       0  607.18     9.8  603.26    49.1  586.51    58.9  584.02    68.8  582.92
    78.6  580.61    88.4  577.47    98.2  575.84     108  575.44   196.4  573.78
   206.2  573.12   211.2572.2563   225.9  569.58   235.7     569   245.5   570.6
   255.4  572.93   265.2  574.44   284.8  575.48   294.6  576.52   304.5  578.81
   314.3  581.58   324.1  583.99   402.7  602.08   422.3  606.96     442  612.17
   451.8  615.32   471.4  622.33   510.7  635.31   540.2   644.1   579.4  654.99
#Mann= 3 , 0 , 0
       0     .06       0   211.2    .045       0   255.4      .1       0
Bank Sta=211.2,255.4
XS Rating Curve= 0 ,0
Exp/Cntr=0.3,0.1

Type RM Length L Ch R = 1 ,5468    ,422.1,427.8,431.7
XS GIS Cut Line= 5
     1675486.583      567097.666     1677721.022      566830.036
     1678833.974      566505.309     1678975.484      566546.965
     1679043.604      565882.569
#Sta/Elev= 30
       0  656.94   147.4   624.5   235.8  649.49   393.1  624.16   491.4  639.62
   678.1  597.04   874.6  584.27  1041.7  629.45  1179.2  678.74  1287.4  694.51
    1366  678.61  1464.2  645.44    1533  659.34  1749.2  683.58  1975.2  673.36
  2073.5  676.08  2230.8   684.6  2358.5  706.31  2446.9  711.23  2525.5  702.93
  2712.2  669.19  2820.3  642.41  2908.7  631.32  3154.3  622.94  3409.8  583.25
  3557.3   581.4  3674.5569.8561  3694.8  567.83  3709.5  570.25  4225.2   592.9
#Mann= 3 , 0 , 0
       0     .06       0  3674.5    .045       0  3709.5     .06       0
Bank Sta=3674.5,3709.5
XS Rating Curve= 0 ,0
Exp/Cntr=0.3,0.1

Type RM Length L Ch R = 1 ,5040.3  ,326.1,326.2,326.1
XS GIS Cut Line= 3
     1677950.292       568628.25     1679164.796      566938.245
     1679503.227      566084.142
#Sta/Elev= 30
       0  664.68   225.8  663.74   382.8  612.07   490.8  601.43   559.6  618.71
   677.4  672.13   893.3  741.42   981.7  780.28  1030.8  794.26  1079.8  800.11
  1148.6  783.68  1276.2  712.54  1403.8  676.11  1492.1  643.71  1560.8  654.35
  1698.3  660.53  1806.3  643.07  1894.6  614.77  1933.9  620.94  2002.6  610.09
  2178.9  619.12  2315.7  611.92  2364.6  593.05    2433  587.51  2459.1570.4575
  2472.1  566.24  2494.1 568.475  2794.6  581.73  2853.2  598.93  2999.8  654.89
#Mann= 3 , 0 , 0
       0     .06       0  2459.1    .045       0  2494.1     .06       0
Bank Sta=2459.1,2494.1
XS Rating Curve= 0 ,0
Exp/Cntr=0.3,0.1

Type RM Length L Ch R = 1 ,4714.1  ,260,259.1,258.5
XS GIS Cut Line= 2
     1679487.521      566963.519     1679762.947      566268.424
#Sta/Elev= 30
       0  639.98    29.5  630.45    78.7  615.12     118  603.46   127.9  601.45
   137.7  600.44   147.6  598.38   157.4  594.43   167.2  589.46   177.1  584.16
   186.9  578.31   197.5571.7279   206.6  567.15   216.4  565.47   226.3  566.94
   236.1  569.69     246  571.16   324.6  572.87   373.8  573.48   521.4  574.81
   531.2  575.38   541.1  577.48   550.9  580.83   639.5  614.93   678.8  630.54
   688.6  633.64   698.5  635.13   708.3  635.28     728  634.28   747.7  632.84
#Mann= 3 , 0 , 0
       0      .1       0   197.5    .045       0   236.1     .06       0
Bank Sta=197.5,236.1
XS Rating Curve= 0 ,0
Exp/Cntr=0.3,0.1

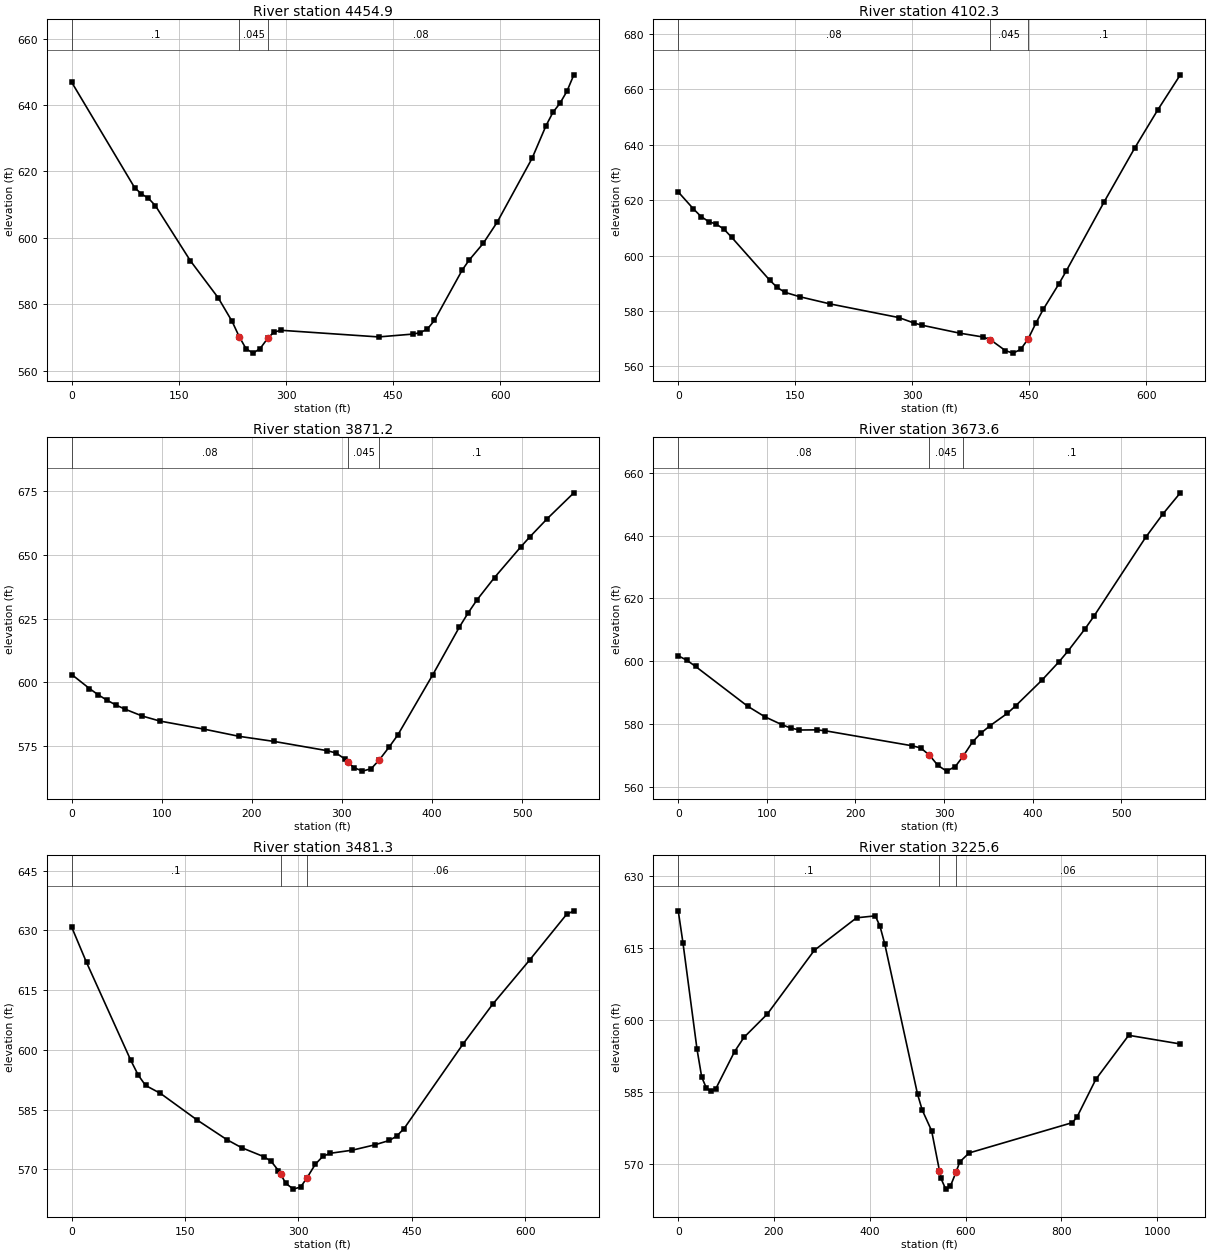
Type RM Length L Ch R = 1 ,4454.9  ,345.5,352.7,359.3
XS GIS Cut Line= 2
     1679731.848      567064.645     1679968.896      566402.979
#Sta/Elev= 30
       0  646.79    87.9  615.12    97.6  613.18   107.4  611.88   117.1  609.65
     166  593.08     205  581.91   224.5  574.79   234.3  570.25     244  566.56
   253.8  565.26   263.6  566.62   274.7569.8414   283.1  571.59   292.8  572.14
   429.5  570.14   478.3  571.01   488.1  571.46   497.8  572.52   507.6   575.1
   546.7  590.34   556.4  593.32   575.9   598.3   595.5   604.7   644.3  623.91
   663.8  633.73   673.6   637.8   683.3  640.48   693.1  644.11   702.8  649.07
#Mann= 3 , 0 , 0
       0      .1       0   234.3    .045       0   274.7     .08       0
Bank Sta=234.3,274.7
XS Rating Curve= 0 ,0
Exp/Cntr=0.3,0.1

Type RM Length L Ch R = 1 ,4102.3  ,227.3,231.1,234.9
XS GIS Cut Line= 2
     1679835.233      567107.436      1680244.26      566610.227
#Sta/Elev= 30
       0  623.01    19.5  616.88    29.3  614.12      39  612.32    48.8  611.37
    58.5   609.6    68.3   606.7   117.1  591.21   126.8  588.56   136.6  586.79
   156.1  585.16   195.1  582.56   282.9  577.66   302.4  575.68   312.2  574.92
   360.9  572.03   390.2  570.67     400  569.72   419.5  565.73   429.2  564.82
     439  566.14   448.7  569.95   458.5  575.59   468.2   580.7   487.8  589.67
   497.5  594.46   546.3  619.51   585.3  638.85   614.6   652.5   643.8  665.29
#Mann= 3 , 0 , 0
       0     .08       0     400    .045       0   448.7      .1       0
Bank Sta=400,448.7
XS Rating Curve= 0 ,0
Exp/Cntr=0.3,0.1

Type RM Length L Ch R = 1 ,3871.2  ,198.8,197.6,196
XS GIS Cut Line= 2
     1679996.324      567178.193     1680416.558      566811.888
#Sta/Elev= 30
       0  603.03    19.6  597.54    29.3  595.08    39.1  592.95    48.9  591.08
    58.7  589.48    78.2  586.73    97.8  584.75   146.7  581.58   185.8  578.74
   224.9  576.72   283.6   573.1   293.4  572.19   303.2  569.85   306.5568.7152
     313  566.48   322.8  565.06   332.5  566.02   341.5569.4914   352.1  574.38
   361.9  579.21     401  603.04   430.3  621.64   440.1  627.24   449.9  632.36
   469.4  641.17   498.8  653.31   508.6  657.14   528.1  664.36   557.5  674.47
#Mann= 3 , 0 , 0
       0     .08       0   306.5    .045       0   341.5      .1       0
Bank Sta=306.5,341.5
XS Rating Curve= 0 ,0
Exp/Cntr=0.3,0.1

Type RM Length L Ch R = 1 ,3673.6  ,196.1,192.3,188.3
XS GIS Cut Line= 2
     1680137.299      567340.477        1680541.      566942.759
#Sta/Elev= 30
       0  601.72     9.8  600.29    19.5  598.34    78.2  585.69    97.7  582.31
   117.2  579.75     127  578.72   136.8  578.08   156.3  578.13   166.1  577.83
   263.8  573.07   273.6  572.39   283.4  570.11   293.1  566.81   302.9  564.99
   312.7  566.44   321.5 569.715   332.2   574.3     342  577.17   351.8  579.42
   371.3  583.35   381.1  585.86   410.4  593.92   429.9  599.85   439.7  603.14
   459.2  610.31     469  614.24   527.6  639.45   547.2  646.93   566.7  653.61
#Mann= 3 , 0 , 0
       0     .08       0   283.4    .045       0   321.5      .1       0
Bank Sta=283.4,321.5
XS Rating Curve= 0 ,0
Exp/Cntr=0.3,0.1

Type RM Length L Ch R = 1 ,3481.3  ,259.4,255.7,252.4
XS GIS Cut Line= 2
     1680293.448      567520.228     1680685.162      566983.434
#Sta/Elev= 30
       0  630.79    19.5  621.98    78.2  597.34      88  593.65    97.7  591.06
   117.3  589.08   166.1  582.36   205.2  577.46   224.8  575.43   254.1  573.18
   263.8  572.02   273.6  569.66   276.3568.7784   283.4  566.46   293.2  565.02
   302.9  565.55   311.3567.8557   322.5  571.31   332.3  573.25     342  574.02
   371.4  574.81   400.7  576.13   420.2  577.24     430  578.34   439.8  580.23
   517.9  601.49     557  611.45   605.9  622.55   654.8  634.02   664.5  634.93
#Mann= 3 , 0 , 0
       0      .1       0   276.3    .045       0   311.3     .06       0
Bank Sta=276.3,311.3
XS Rating Curve= 0 ,0
Exp/Cntr=0.3,0.1

Type RM Length L Ch R = 1 ,3225.6  ,309.7,302.1,294.6
XS GIS Cut Line= 2
     1680388.463       567969.68     1680858.278      567032.278
#Sta/Elev= 30
       0  622.79     9.8  616.16    39.2   593.9      49  588.07    58.8  585.76
    68.6  585.08    78.4  585.62   117.6  593.38   137.2  596.35   186.2  601.25
   284.2  614.54   372.4  621.33   411.6  621.74   421.4  619.56   431.2  615.92
   499.8  584.49   509.6  581.17   529.2  576.85   545.6568.4998   548.8  566.89
   558.6  564.66   568.4  565.27   580.6568.3112     588  570.35   607.6  572.22
   823.2  578.55     833  579.75   872.2   587.6   940.8  596.79  1048.6  594.98
#Mann= 3 , 0 , 0
       0      .1       0   545.6    .045       0   580.6     .06       0
Bank Sta=545.6,580.6
XS Rating Curve= 0 ,0
Exp/Cntr=0.3,0.1

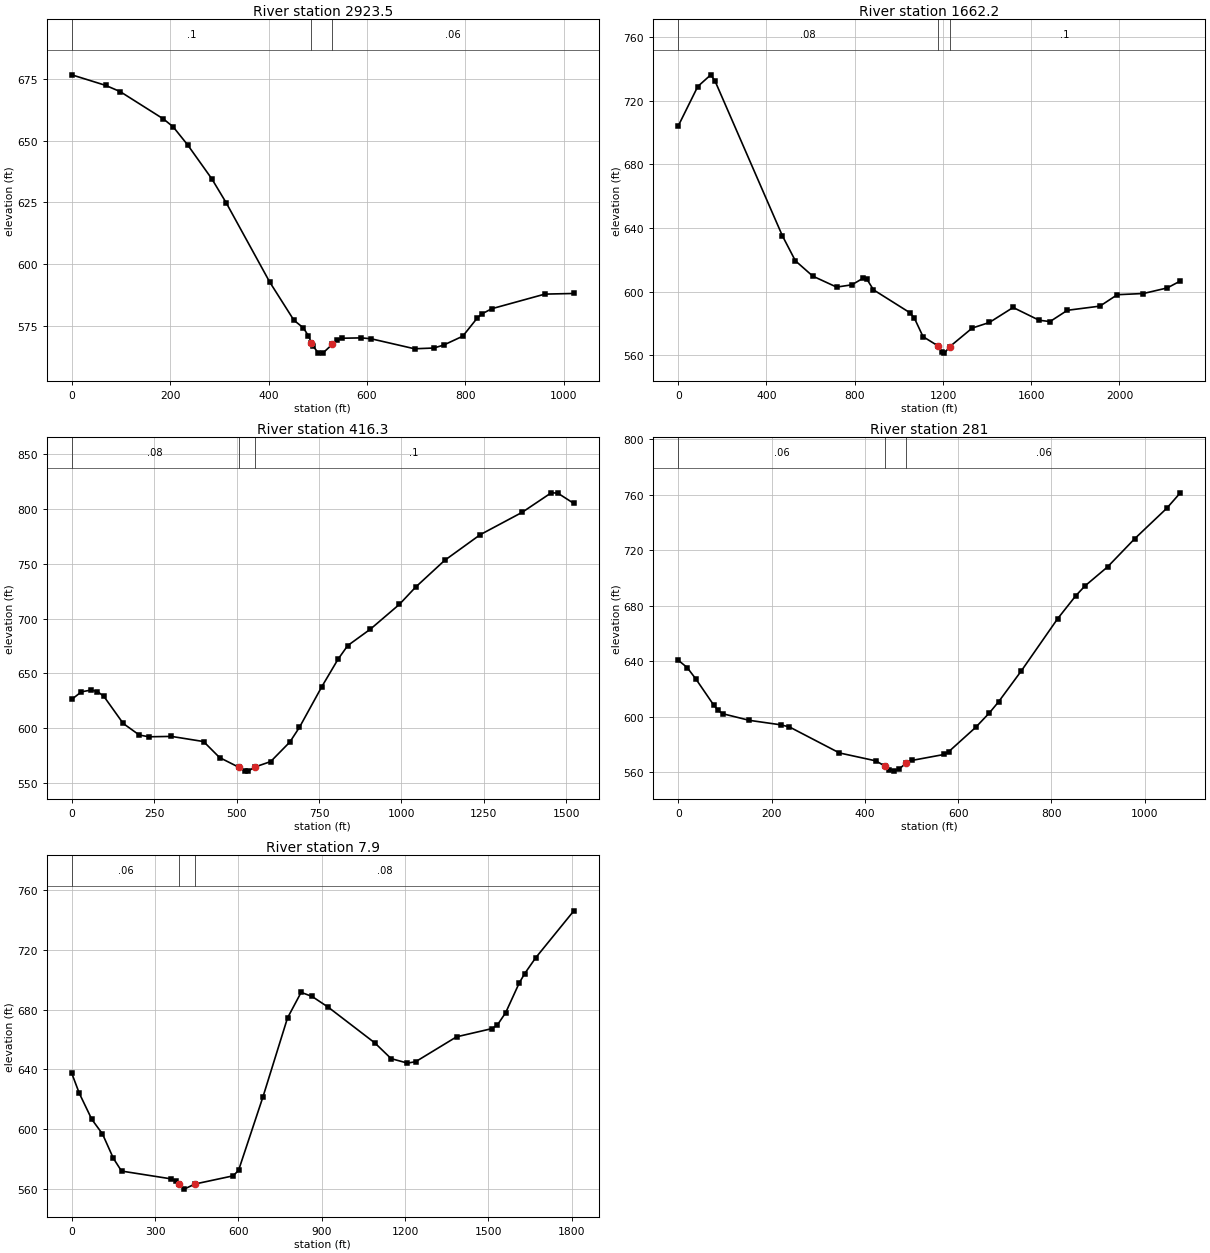
Type RM Length L Ch R = 1 ,2923.5  ,1284.9,1261.3,1236
XS GIS Cut Line= 2
     1680854.346      568080.372     1680986.461      567068.445
#Sta/Elev= 30
       0  676.58    68.7  672.32    98.1  669.82   186.4  658.71   206.1  655.53
   235.5  648.24   284.6  634.51     314  624.76   402.3  592.74   451.4  577.31
     471  574.13   480.8  570.99   487.2568.2406   490.6  566.78   500.4  564.22
   510.3  563.97   529.9   567.6   539.7  569.34   549.5     570   588.8  570.14
   608.4  569.78   696.7  565.73     736  566.04   755.6  567.21   794.8  570.83
   824.3  578.21   834.1   579.9   853.7  581.94   961.6  587.85  1020.5  588.11
#Mann= 3 , 0 , 0
       0      .1       0   487.2    .045       0   529.9     .06       0
Bank Sta=487.2,529.9
XS Rating Curve= 0 ,0
Exp/Cntr=0.3,0.1

Type RM Length L Ch R = 1 ,1662.2  ,1214.4,1245.9,1277.5
XS GIS Cut Line= 4
     1681723.249      568131.171     1681557.785      567141.886
     1681198.326      566894.683     1680663.527      566251.365
#Sta/Elev= 30
       0  704.07    88.5  728.83   147.5  736.17   167.2  732.16     472  635.16
     531  619.44   609.7  609.83   717.8  602.94   786.7  604.34   835.9  608.33
   855.5  607.82     885  601.22  1051.5  586.72  1070.9   583.3  1109.7  571.82
  1177.5  566.02  1196.9  561.89  1206.6  561.48  1229.7565.3973  1332.6  577.22
  1410.2  580.71    1518  590.13  1636.1  582.11  1685.3   581.3  1764.1  588.37
  1911.7  590.99  1990.4  598.16  2108.6   598.9  2216.8  602.41  2275.9  606.75
#Mann= 3 , 0 , 0
       0     .08       0  1177.5    .045       0  1229.7      .1       0
Bank Sta=1177.5,1229.7
XS Rating Curve= 0 ,0
Exp/Cntr=0.3,0.1

Type RM Length L Ch R = 1 ,416.3   ,130,135.3,140.3
XS GIS Cut Line= 4
     1681653.516      567422.385     1681695.897      567044.245
     1681839.585      566726.265     1681800.452      565933.483
#Sta/Elev= 30
       0  626.28    29.3  633.16    58.5  634.72      78  633.39    97.6  628.91
   156.1  604.26   204.9  593.71   234.2  592.12   302.4  592.47   399.9  587.77
   448.4  573.18   506.5  564.37   525.9  560.79   535.6  560.82   554.6564.4376
   603.4   569.5   661.6  587.31   690.7  600.74   758.8  637.94   807.8  662.88
   837.2  675.32   905.8  690.27     994  712.94    1043   728.6  1131.2  753.05
    1239  776.46  1366.4   796.9  1454.6  814.68  1474.2  814.46  1523.2  804.99
#Mann= 3 , 0 , 0
       0     .08       0   506.5    .045       0   554.6      .1       0
Bank Sta=506.5,554.6
XS Rating Curve= 0 ,0
Exp/Cntr=0.3,0.1

Type RM Length L Ch R = 1 ,281     ,264.7,273.1,282
XS GIS Cut Line= 4
     1681697.587        567375.7     1681744.189       567141.95
     1681924.787      566899.717     1681928.635      566363.807
#Sta/Elev= 30
       0   640.7    19.1   635.4    38.1     627    76.3   608.2    85.8  604.43
    95.3  602.07   152.5  597.29   219.3  594.09   238.4  592.53   345.6  573.76
   423.5  568.06     443  564.31   452.8   561.8   462.5  560.64   472.3  561.82
   489.1566.5771   501.5   568.4   569.7  572.65   579.5  574.56   637.9  592.31
   667.2  602.71   686.7  610.64   735.4  632.92   813.3   670.6   852.3  687.22
   871.8  694.23   920.5  708.06     979   728.5  1047.2   750.3  1076.4  761.49
#Mann= 3 , 0 , 0
       0     .06       0     443    .045       0   489.1     .06       0
Bank Sta=443,489.1
XS Rating Curve= 0 ,0
Exp/Cntr=0.3,0.1

Type RM Length L Ch R = 1 ,7.9     ,0,7.9,16.3
XS GIS Cut Line= 4
      1681737.85      567399.611     1681756.358      567320.553
      1682399.43      566945.028     1682803.664      566050.066
#Sta/Elev= 30
       0  637.22    27.1  623.85    72.2  606.37   110.6  596.62   149.8  580.28
   179.2  571.74   355.6  566.58   375.2  565.32   386.3563.0139   404.6  559.64
   443.7  563.07   580.9  568.54   600.5  572.18   688.7   621.6   776.9  674.37
   825.9  691.48   865.2  688.76   924.1  681.47    1091  657.65    1150  647.08
  1208.9  644.08  1238.3  645.03  1385.6   661.7  1513.3  667.21  1532.9  669.72
  1562.4  677.87  1611.5  697.88  1631.1  704.11  1670.4  714.63  1807.9  746.12
#Mann= 3 , 0 , 0
       0     .06       0   386.3    .045       0   443.7     .08       0
Bank Sta=386.3,443.7
XS Rating Curve= 0 ,0
Exp/Cntr=0.3,0.1

Chan Stop Cuts=-1
Use User Specified Reach Order=0
Composite Channel Slope=5